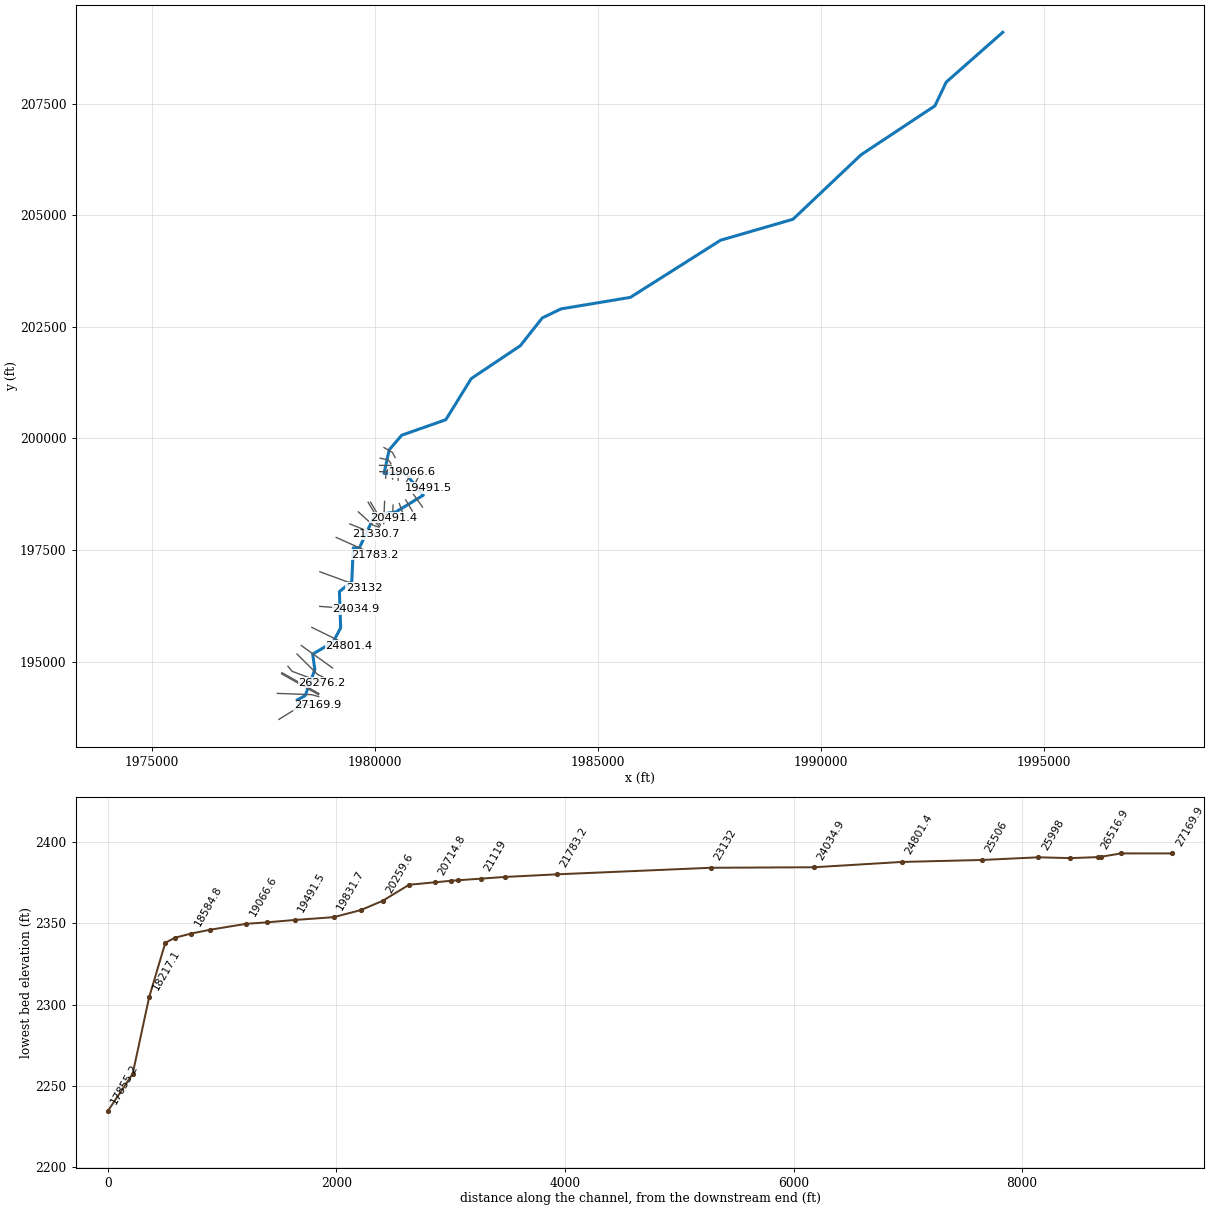
--- PIPESTCK.prj (project) ---

Proj Title=PIPESTCK
Current Plan=p01
Default Exp/Contr=0,0
English Units
Geom File=g01
Flow File=f01
Plan File=p01
BEGIN DESCRIPTION:
END DESCRIPTION:
DSS Export Rating Curves= 0
DSS Export Rating Curve Sorted= 0
DSS Export Volume Flow Curves= 0
DXF OffsetX= 0
DXF OffsetY= 0
DXF ScaleX= 0
DXF ScaleY= 0

--- PIPESTCK.p01 (plan) ---

Plan Title=Floodplain
Program Version=4.00
Geom File=g01
Flow File=f01
K Sum by GR=0
Std Step Tol=0.01
Critical Tol=0.01
Num of Std Step Trials=20
Max Error Tol=0.3
Flow Tol Ratio=0.001
Split Flow NTrial=30
Split Flow Tol=0.02
Split Flow Ratio=0.02
Log Output Level=0
Friction Slope Method=1
Unsteady Friction Slope Method=2
Unsteady Bridges Friction Slope Method=1
Global Log Level=0
CheckData=False
Run HTab=0
Run UNet=0
Run PostProcess=0
UNET Theta=0
UNET Theta Warmup=0
UNET ZTol=0
UNET ZSATol=0
UNET MxIter=0
UNET MaxInSteps=0
UNET DtIC=0
UNET DtMin=0
UNET MaxCRTS=0
UNET WFStab=0
UNET SFStab=0
UNET WFX=0
UNET SFX=0
UNET DSS MLevel=0
UNET DZMax Abort=0
UNET Convert EG Bridges=0
UNET Use Existing IB Tables=0
UNET Froude Limit=0
UNET Froude Power=0
Write IC File=0
Echo Input=False
Echo Output=False
Write Detailed=0

--- PIPESTCK.f01 (steady flow) ---

Flow Title=2010 USGS WV Regression Equation
Program Version=5.03
Number of Profiles= 1
Profile Names=P100yr
River Rch & RM=PIPESTCK,Main            ,27169.9
505.2999
River Rch & RM=PIPESTCK,Main            ,26720.8
505.3746
River Rch & RM=PIPESTCK,Main            ,26276.2
717.2589
River Rch & RM=PIPESTCK,Main            ,24801.4
780.3663
River Rch & RM=PIPESTCK,Main            ,23132
829.7194
River Rch & RM=PIPESTCK,Main            ,20918.7
895.2061
River Rch & RM=PIPESTCK,Main            ,15911
983.1546
River Rch & RM=PIPESTCK,Main            ,14870.9
1152.223
River Rch & RM=PIPESTCK,Main            ,12711.1
1228.424
River Rch & RM=PIPESTCK,Main            ,7361.4
1345.861
River Rch & RM=PIPESTCK,Main            ,7066.5
 1672.66
River Rch & RM=PIPESTCK,Main            ,6180.6
1702.524
River Rch & RM=PIPESTCK,Main            ,4372.9
1881.393
River Rch & RM=PIPESTCK,Main            ,150.3
2016.862
Boundary for River Rch & Prof#=PIPESTCK,Main            , 1
Up Type= 0
Dn Type= 1
Dn Known WS=1684.5
DSS Import GetInterval= 0
DSS Import GetPeak= 0
DSS Import FillOption= 0

--- PIPESTCK.g01 (geometry) ---

Geom Title=LiDAR
Program Version=4.10

River Reach=PIPESTCK        ,Main
Reach XY= 30
     1978324.091      193959.454      1978250.48      194132.718
     1978439.021       194233.76     1978656.035      194817.093
     1978607.654      195165.358     1979066.749      195437.033
     1979234.616      195756.025     1979206.491      196566.442
     1979484.095      196794.567     1979517.158      197546.772
     1979655.159      197548.209     1979995.232       198273.76
     1980475.319      198354.837     1981087.224       198727.37
     1980681.495      199222.683     1980207.133      199216.816
      1980322.12      199743.516     1980603.077      200072.382
     1981591.786      200420.219     1982161.703      201341.954
     1983262.745      202079.454     1983754.411       202701.85
     1984174.724      202904.454     1985727.849      203162.266
     1987752.328      204444.037     1989374.724      204913.829
     1990899.909       206358.69     1992555.924      207456.078
     1992809.326       207987.45     1994076.764      209104.711

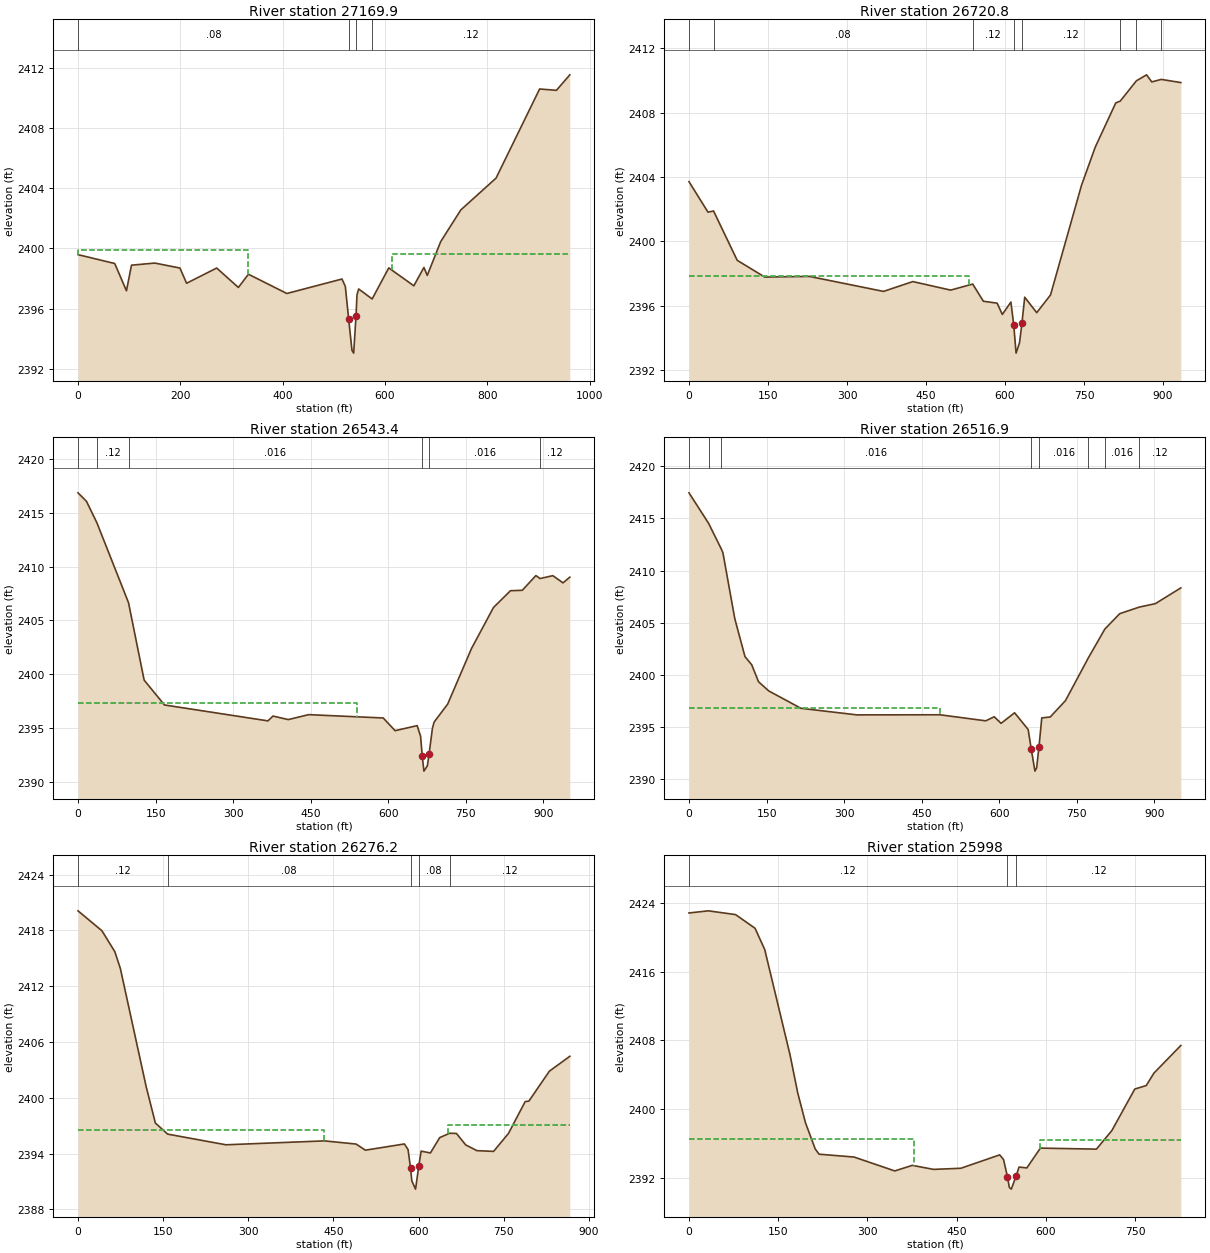
Type RM Length L Ch R = 1 ,27169.9 ,462,449,427.7
XS GIS Cut Line= 3
     1977849.304      193701.855     1978396.179      194040.397
     1978713.019      194014.355
#Sta/Elev= 30
       0 2399.58    71.8 2398.99    94.7 2397.18   104.5 2398.88   150.2 2399.02
   199.2 2398.69   212.2 2397.68     271 2398.69   313.4  2397.4     333 2398.28
   408.1    2397   515.8 2397.96   522.4 2397.47   528.9 2395.31   535.4 2393.22
   538.7 2393.04  543.242395.489   545.2 2396.91   548.5  2397.3  574.812396.637
   607.3  2398.7   656.3 2397.51     676 2398.73   682.5  2398.2   708.7 2400.44
   748.1 2402.55   816.9 2404.66   902.1 2410.58   934.9 2410.49   961.1 2411.52
#Mann= 4 ,-1 , 0
       0     .08       0   528.9    .045       0  543.24     .08       0
  574.81     .12       0
#XS Ineff= 2 , 0
          331.27 2399.92  614.04         2399.63
Permanent Ineff=
       F       F
Bank Sta=528.9,543.24
XS Rating Curve= 0 ,0
Exp/Cntr=0.3,0.1

Type RM Length L Ch R = 1 ,26720.8 ,185.8,177.5,149.2
XS GIS Cut Line= 3
     1977815.428      194285.297     1978586.261      194256.651
     1978742.511       194212.38
#Sta/Elev= 30
       0 2403.71      36 2401.82   46.652401.889    91.5 2398.83   143.8 2397.79
   228.8 2397.83   369.3  2396.9   424.9 2397.51   496.8 2396.98  538.632397.356
   558.9 2396.29   585.1 2396.17   594.9 2395.47   611.2 2396.24  616.582394.814
     621 2393.07   627.6 2393.72  632.072394.916   637.4 2396.54   660.2 2395.58
   686.4 2396.68   745.2 2403.48   771.4 2405.86   810.3  2408.6  818.762408.709
  849.46 2409.97   868.8 2410.34   878.6  2409.9  896.712410.056   933.8 2409.86
#Mann= 8 ,-1 , 0
       0     .12       0   46.65     .08       0  538.63     .12       0
  616.58    .045       0  632.07     .12       0  818.76     .06       0
  849.46    .016       0  896.71     .12       0
#XS Ineff= 2 , 0
          532.51 2397.84
Permanent Ineff=
       F       F
Bank Sta=616.58,632.07
XS Rating Curve= 0 ,0
Exp/Cntr=0.3,0.1

Type RM Length L Ch R = 1 ,26543.4 ,27.9,26.5,26.7
XS GIS Cut Line= 2
      1977909.59      194724.867     1978737.586      194257.186
#Sta/Elev= 30
       0 2416.86    16.4 2416.07   36.632414.065   97.672406.648   127.9 2399.45
   167.2 2397.14   367.3 2395.66   377.1 2396.11   406.6 2395.78     446 2396.24
   590.2 2395.93   613.2 2394.75   655.8 2395.22   662.4 2394.24   665.7 2392.36
   668.9 2390.99   675.5 2391.48   678.8 2392.55   685.3 2394.97   688.6 2395.55
   714.8 2397.22   760.8 2402.38   803.4  2406.2   836.2 2407.76   859.1  2407.8
   885.4 2409.17  893.392408.891   918.2 2409.16   937.8 2408.49     951 2409.02
#Mann= 6 ,-1 , 0
       0     .06       0   36.63     .12       0   97.67    .016       0
   665.7    .045       0   678.8    .016       0  893.39     .12       0
#XS Ineff= 2 , 0
           538.7  2397.3
Permanent Ineff=
       F       F
Bank Sta=665.7,678.8
XS Rating Curve= 0 ,0
Exp/Cntr=0.3,0.1

Type RM Length L Ch R = 1 ,26516.9 ,234.5,240.6,244
XS GIS Cut Line= 2
     1977919.138      194749.172     1978747.135      194281.491
#Sta/Elev= 30
       0 2417.46   37.862414.538   62.542412.072    65.6 2411.71    88.5 2405.41
   108.2 2401.77   121.3 2400.98   134.4 2399.36   154.1 2398.48   216.4 2396.81
   324.6 2396.18   485.3 2396.19   573.8 2395.61   590.2    2396   603.4 2395.37
   629.6 2396.38   655.8 2394.78   661.7 2392.93   668.9 2390.79   672.2  2391.1
   676.7  2393.1   682.1 2395.89   698.5 2395.98     728 2397.55  772.212401.646
  804.172404.409   832.9 2405.88  870.66 2406.51   901.8 2406.84     951 2408.35
#Mann= 8 ,-1 , 0
       0     .06       0   37.86     .12       0   62.54    .016       0
   661.7    .045       0   676.7    .016       0  772.21     .12       0
  804.17    .016       0  870.66     .12       0
#XS Ineff= 2 , 0
          486.07 2396.84
Permanent Ineff=
       F       F
Bank Sta=661.7,676.7
XS Rating Curve= 0 ,0
Exp/Cntr=0.3,0.1

Type RM Length L Ch R = 1 ,26276.2 ,286.2,278.2,263.8
XS GIS Cut Line= 3
     1978052.407      194892.068     1978146.157      194780.089
     1978820.636      194527.484
#Sta/Elev= 30
       0 2420.11    42.2 2417.96    64.9 2415.71    74.6 2413.91   120.1 2401.18
   136.3 2397.28  157.882396.089   260.6 2394.94   434.1 2395.36   489.8 2395.02
   506.2 2394.36   574.9 2395.03   581.4 2394.42  585.682392.435     588 2391.05
   594.6 2390.17  600.182392.636   604.4 2394.26   620.7 2394.06   637.1 2395.71
  654.47 2396.18   666.6 2396.16   682.9 2394.93   702.6 2394.31     732 2394.23
   758.2 2396.16   787.7 2399.59   794.2 2399.64   830.3 2402.86   866.3 2404.46
#Mann= 5 ,-1 , 0
       0     .12       0  157.88     .08       0  585.68    .045       0
  600.18     .08       0  654.47     .12       0
#XS Ineff= 2 , 0
          433.44  2396.5  651.19         2397.04
Permanent Ineff=
       F       F
Bank Sta=585.68,600.18
XS Rating Curve= 0 ,0
Exp/Cntr=0.3,0.1

Type RM Length L Ch R = 1 ,25998   ,470.2,492.1,490.8
XS GIS Cut Line= 3
     1978255.573       195168.11     1978713.907      194712.381
     1978875.365      194631.652
#Sta/Elev= 30
       0 2422.86    32.6 2423.11    78.3 2422.67     111 2421.08   127.3  2418.6
   169.8 2406.35   182.8 2401.89   195.9  2398.4   212.2 2395.36   218.7 2394.75
   277.5 2394.42     346  2392.8   375.4 2393.45   411.3 2392.98     457 2393.11
   522.3 2394.67   528.8 2394.13   535.4 2392.13   538.6 2390.87   541.9 2390.68
  549.812392.189   554.9 2393.25     568 2393.15   590.8 2395.46     685 2395.34
   710.8 2397.49   749.5 2402.34   768.8 2402.75   781.7  2404.2   826.9 2407.42
#Mann= 3 , 0 , 0
       0     .12       0   535.4    .045       0  549.81     .12       0
#XS Ineff= 2 , 0
          378.74  2396.5   590.3         2396.39
Permanent Ineff=
       F       F
Bank Sta=535.4,549.81
XS Rating Curve= 0 ,0
Exp/Cntr=0.3,0.1

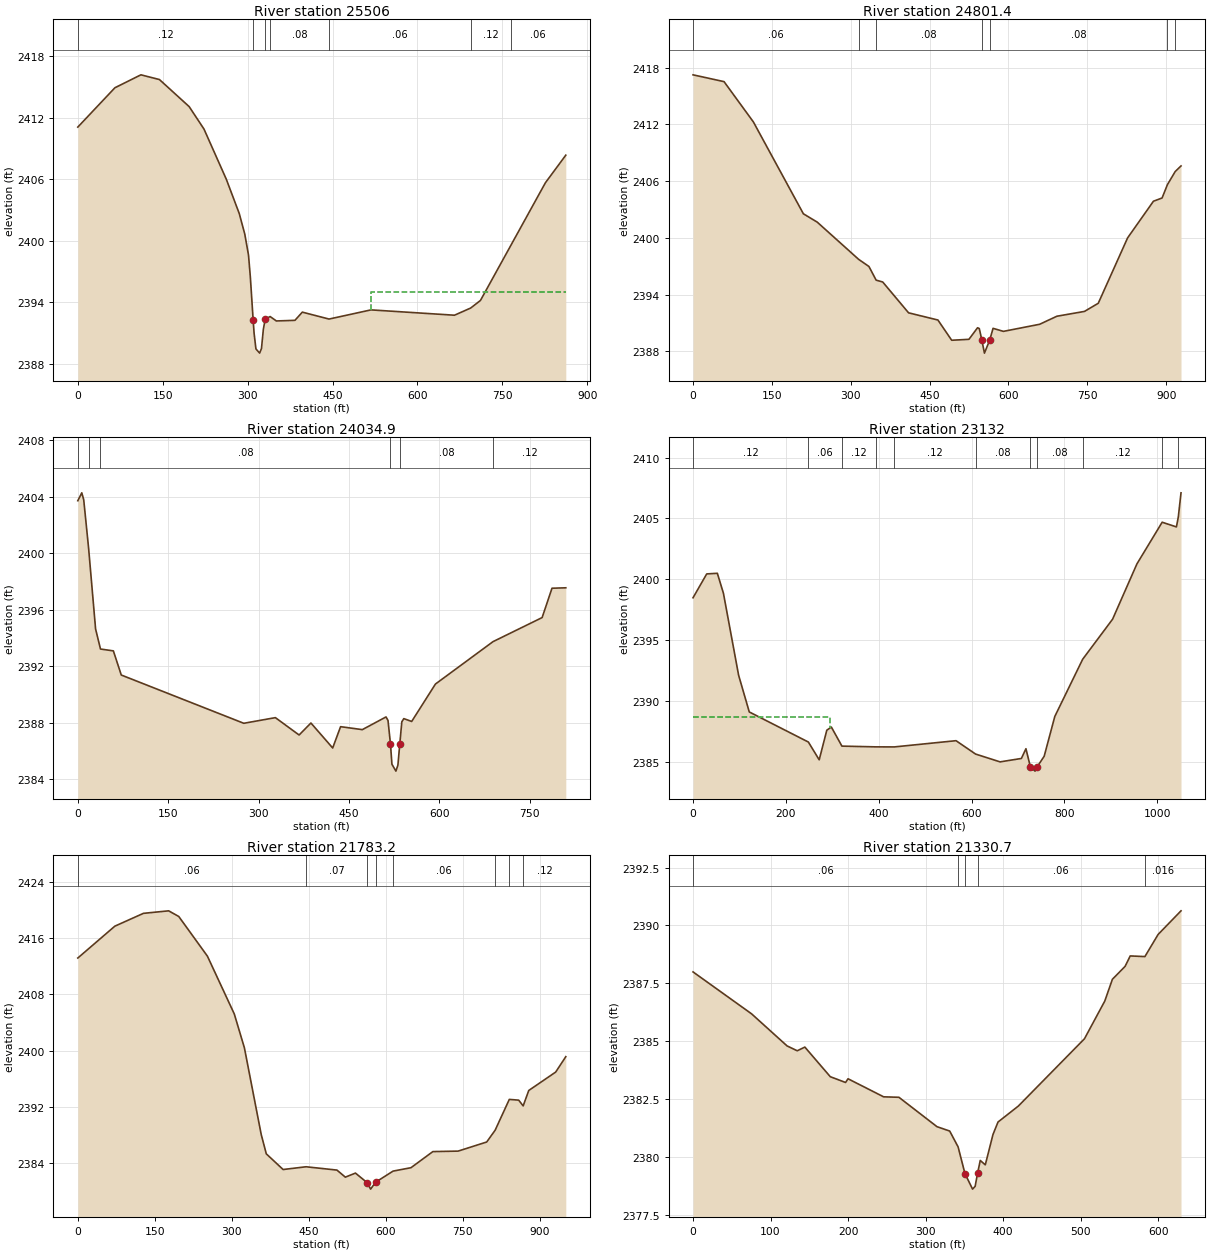
Type RM Length L Ch R = 1 ,25506   ,713.1,704.6,694.3
XS GIS Cut Line= 2
     1978351.886      195358.214     1979052.407      194855.609
#Sta/Elev= 30
       0  2411.1    65.6 2414.94   111.5  2416.2   144.2 2415.74   196.7  2413.1
   222.9 2410.91   262.3 2406.02   285.2 2402.67     295 2400.66   301.6 2398.61
   304.9 2396.42  309.772392.294   311.4 2391.01   314.7 2389.45   321.3 2389.04
   324.5 2389.49   327.8 2391.36   331.1 2392.35  339.76 2392.61   350.8 2392.18
   383.6 2392.24   396.7 2393.04  443.862392.365     518 2393.26   665.5 2392.74
  694.172393.442   711.4 2394.18  764.842399.528   826.1 2405.66   862.2 2408.36
#Mann= 7 ,-1 , 0
       0     .12       0  309.77    .045       0   331.1     .12       0
  339.76     .08       0  443.86     .06       0  694.17     .12       0
  764.84     .06       0
#XS Ineff= 2 , 0
                          518.06         2394.99
Permanent Ineff=
       F       F
Bank Sta=309.77,331.1
XS Rating Curve= 0 ,0
Exp/Cntr=0.3,0.1

Type RM Length L Ch R = 1 ,24801.4 ,755.7,766.5,772.8
XS GIS Cut Line= 2
     1978588.866      195764.464     1979422.199      195355.609
#Sta/Elev= 30
       0 2417.24      59 2416.52   114.8 2412.26   209.9 2402.55   236.2 2401.67
  314.992397.735   334.6 2396.98  348.312395.534   360.8 2395.34     410 2392.08
   465.8 2391.32     492 2389.18   524.8 2389.28   541.2  2390.5   544.5 2390.42
  549.362389.196   554.3 2387.82   564.2 2389.18   570.7 2390.44   590.4 2390.12
   659.3 2390.87   692.1 2391.72   744.6 2392.23   770.8 2393.09   826.6    2400
   875.8 2403.88   892.2 2404.22   902.32405.626  917.092407.011   928.2 2407.61
#Mann= 7 ,-1 , 0
       0     .06       0  314.99     .12       0  348.31     .08       0
  549.36    .045       0   564.2     .08       0   902.3     .12       0
  917.09    .016       0
Bank Sta=549.36,564.2
XS Rating Curve= 0 ,0
Exp/Cntr=0.3,0.1

Type RM Length L Ch R = 1 ,24034.9 ,818.2,902.8,827.3
XS GIS Cut Line= 2
     1978765.949      196235.818     1979573.241      196173.318
#Sta/Elev= 30
       0 2403.72     6.6 2404.28     9.8 2403.79   17.942400.343    29.5 2394.63
   37.632393.212      59 2393.08    72.1 2391.37   275.4 2387.95   327.8 2388.35
   367.2 2387.12   386.8 2387.97   422.9  2386.2     436 2387.71   472.1  2387.5
   511.4  2388.4   514.7 2388.15  518.812386.476   521.2 2385.05   527.8 2384.56
   531.1 2384.98   534.3 2386.51   537.6 2388.05   540.9 2388.28     554 2388.08
   593.4 2390.73  688.942393.735   770.4 2395.44   786.8 2397.52   809.7 2397.55
#Mann= 6 ,-1 , 0
       0     .04       0   17.94     .12       0   37.63     .08       0
  518.81    .045       0   534.3     .08       0  688.94     .12       0
Bank Sta=518.81,534.3
XS Rating Curve= 0 ,0
Exp/Cntr=0.3,0.1

Type RM Length L Ch R = 1 ,23132   ,1300.3,1348.9,1065.6
XS GIS Cut Line= 2
     1978768.553      197011.859     1979755.532       196649.88
#Sta/Elev= 30
       0 2398.48    29.5 2400.44    52.4 2400.49    65.5 2398.85    98.2 2392.12
   121.2  2389.1   248.52386.629   271.8 2385.17   288.2  2387.6     298 2387.86
  320.792386.294  393.612386.233  433.772386.229   566.6 2386.74  608.762385.641
   661.5    2385   707.4 2385.28   717.2 2386.08     727 2384.56   736.9 2384.24
  740.952384.567   756.5 2385.46   779.4 2388.73  839.462393.431   903.9 2396.72
   956.3 2401.26  1010.72404.685  1041.4  2404.3  1045.52405.121  1051.3  2407.1
#Mann= 11 ,-1 , 0
       0     .12       0   248.5     .06       0  320.79     .12       0
  393.61     .06       0  433.77     .12       0  608.76     .08       0
     727    .045       0  740.95     .08       0  839.46     .12       0
  1010.7    .016       0  1045.5     .12       0
#XS Ineff= 2 , 0
          294.74 2388.72
Permanent Ineff=
       F       F
Bank Sta=727,740.95
XS Rating Curve= 0 ,0
Exp/Cntr=0.3,0.1

Type RM Length L Ch R = 1 ,21783.2 ,448.4,452.5,449.8
XS GIS Cut Line= 2
     1979134.438      197781.521     1980002.494      197392.632
#Sta/Elev= 30
       0 2413.21    72.2 2417.76   127.9 2419.59   177.1 2419.95   196.8 2419.14
   252.6 2413.48     305 2405.22   324.7 2400.39   357.5    2388   367.4 2385.24
   400.2    2383  444.912383.393   505.1 2382.92   521.5 2381.91   541.2 2382.49
   564.2 2381.11   570.7  2380.2   580.6 2381.19  614.512382.774   649.4 2383.26
   692.1 2385.56   741.3 2385.63     797 2386.93  813.45 2388.61  841.082393.015
   859.4 2392.91  868.092392.085     879 2394.29   931.5 2396.92   951.2 2399.12
#Mann= 8 ,-1 , 0
       0     .06       0  444.91     .07       0   564.2    .045       0
   580.6     .07       0  614.51     .06       0  813.45     .08       0
  841.08    .016       0  868.09     .12       0
Bank Sta=564.2,580.6
XS Rating Curve= 0 ,0
Exp/Cntr=0.3,0.1

Type RM Length L Ch R = 1 ,21330.7 ,218.8,211.7,202.6
XS GIS Cut Line= 2
     1979440.862      198083.604     1980024.195      197847.493
#Sta/Elev= 30
       0 2387.99    75.4 2386.18   121.3 2384.79   134.4 2384.58   144.2 2384.74
     177 2383.46   196.7 2383.21   199.9 2383.37   245.8 2382.59   265.5 2382.57
   314.6  2381.3     331 2381.11  341.822380.427   350.7 2379.27   360.5  2378.6
   363.8 2378.72   367.1 2379.31   370.4 2379.84   376.9 2379.65   386.8 2380.96
   393.3  2381.5   419.5 2382.19   504.8  2385.1     531 2386.73   540.8 2387.67
   557.2 2388.23   563.8 2388.68  582.722388.652   599.8 2389.61   629.3 2390.63
#Mann= 5 ,-1 , 0
       0     .06       0  341.82     .12       0   350.7    .045       0
   367.1     .06       0  582.72    .016       0
Bank Sta=350.7,367.1
XS Rating Curve= 0 ,0
Exp/Cntr=0.3,0.1

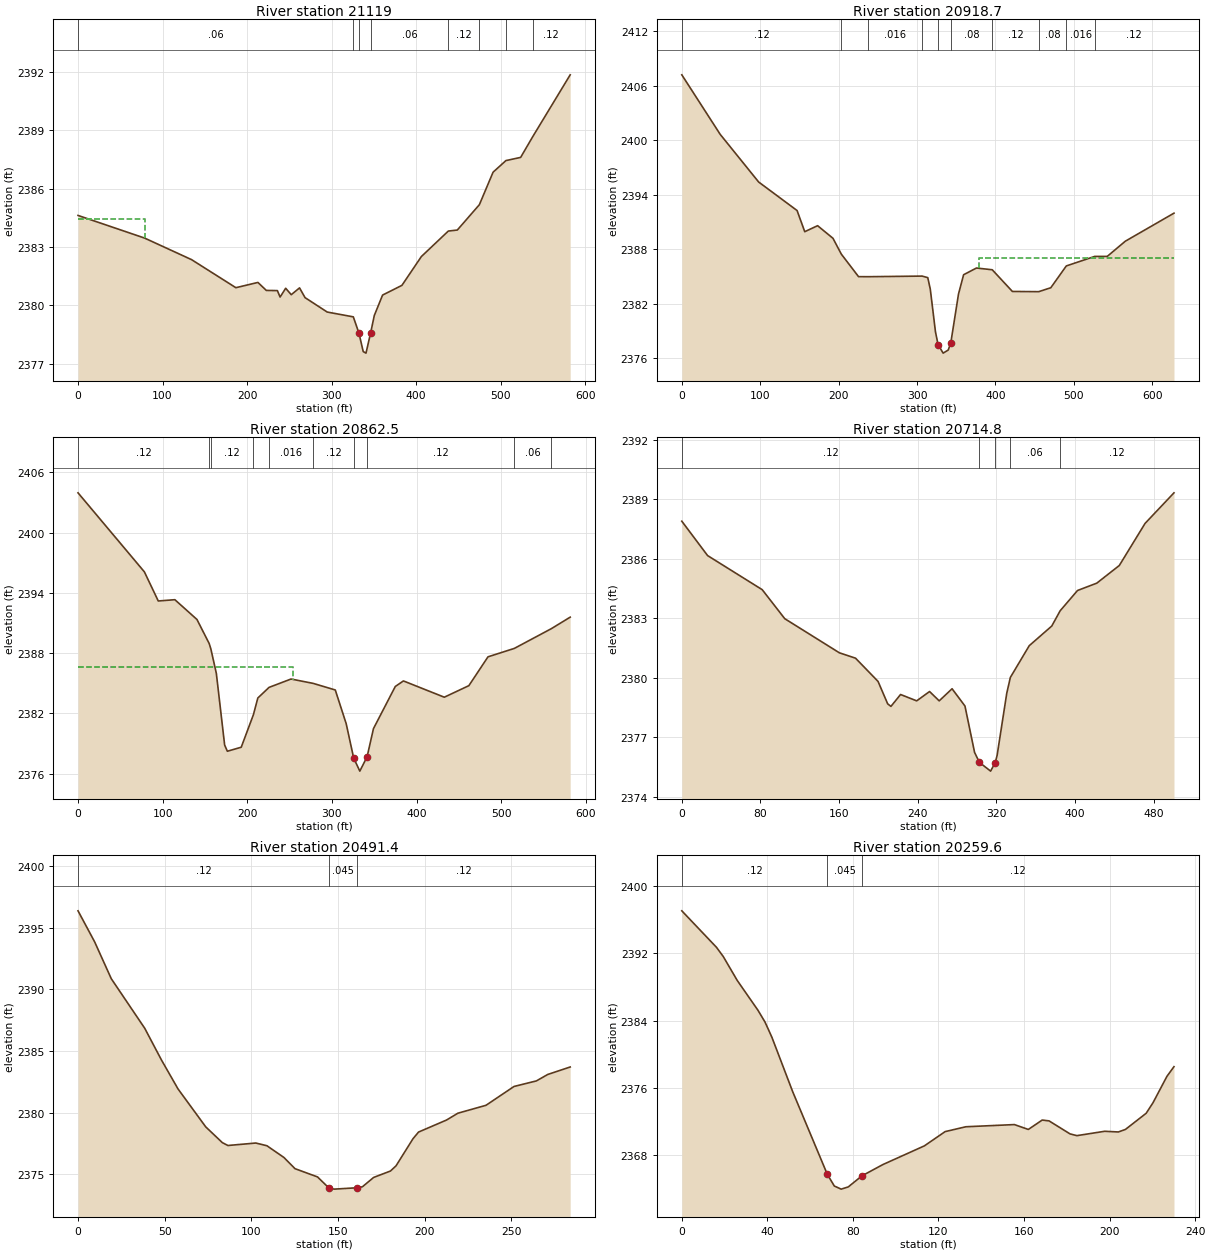
Type RM Length L Ch R = 1 ,21119   ,221.5,200.3,176.8
XS GIS Cut Line= 3
     1979631.545      198353.208     1979953.811      198060.239
     1980091.614      198010.326
#Sta/Elev= 30
       0 2384.62    78.6 2383.46   134.3 2382.35   186.7 2380.91   212.8 2381.18
   222.7 2380.77   235.8 2380.76     239 2380.43   245.6 2380.88   252.2 2380.55
     262  2380.9   268.5  2380.4   294.7 2379.66   325.62379.412   332.3 2378.57
   337.3 2377.63   340.6 2377.55  346.122378.598   350.4 2379.48   360.2 2380.53
   383.1 2381.03   406.1 2382.51  437.982383.818   448.6 2383.87  474.692385.172
   490.9 2386.84   506.12387.437   523.5  2387.6  537.522388.644   582.1 2391.84
#Mann= 8 ,-1 , 0
       0     .06       0   325.6     .12       0   332.3    .045       0
  346.12     .06       0  437.98     .12       0  474.69    .016       0
   506.1     .06       0  537.52     .12       0
#XS Ineff= 2 , 0
           79.26 2384.46
Permanent Ineff=
       F       F
Bank Sta=332.3,346.12
XS Rating Curve= 0 ,0
Exp/Cntr=0.3,0.1

Type RM Length L Ch R = 1 ,20918.7 ,56.2,56.2,55.8
XS GIS Cut Line= 4
     1979850.729      198569.137     1980009.149      198302.209
     1979996.186      198142.523      1980105.72      198029.857
#Sta/Elev= 30
       0  2407.2      49 2400.64      98  2395.4     147 2392.26   156.8 2389.93
   173.2 2390.59   192.8  2389.2  203.44 2387.46   225.4 2384.98  237.792384.974
  306.492385.041   313.7 2384.87   316.9 2383.61   323.5 2378.91   326.8  2377.5
   333.3 2376.56   339.8  2376.9   343.1 2377.71   352.9 2383.07   359.4 2385.19
   375.8 2385.93  395.932385.738   421.6 2383.35   455.22383.326   470.6 2383.76
  490.39 2386.16  526.66 2387.21   542.6 2387.21   565.6 2388.88   627.7 2391.97
#Mann= 10 ,-1 , 0
       0     .12       0  203.44     .06       0  237.79    .016       0
  306.49     .08       0   326.8    .045       0   343.1     .08       0
  395.93     .12       0   455.2     .08       0  490.39    .016       0
  526.66     .12       0
#XS Ineff= 2 , 0
                          378.53         2387.06
Permanent Ineff=
       F       F
Bank Sta=326.8,343.1
XS Rating Curve= 0 ,0
Exp/Cntr=0.3,0.1

Type RM Length L Ch R = 1 ,20862.5 ,145.8,147.6,149.3
XS GIS Cut Line= 4
     1979904.982      198572.392     1980063.403      198305.465
     1980051.686      198161.133     1980127.422      198060.239
#Sta/Elev= 30
       0 2403.97    78.4  2396.1    94.8  2393.2   114.4 2393.33   140.5 2391.36
  154.922388.969  156.95 2388.42   163.4 2385.99   173.2 2378.86   176.4 2378.24
   192.8 2378.64  207.222381.889   212.4 2383.54  225.682384.599   251.6 2385.43
  277.782384.997   303.9 2384.34   316.8 2380.98  325.612377.569   332.9 2376.26
  341.492377.695     349 2380.49   374.8 2384.69   384.4 2385.24   432.7 2383.62
   461.7 2384.77   484.3 2387.64  515.392388.478   559.12390.443   581.4 2391.59
#Mann= 10 ,-1 , 0
       0     .12       0  154.92     .06       0  156.95     .12       0
  207.22     .06       0  225.68    .016       0  277.78     .12       0
  325.61    .045       0  341.49     .12       0  515.39     .06       0
   559.1     .12       0
#XS Ineff= 2 , 0
          254.49 2386.66
Permanent Ineff=
       F       F
Bank Sta=325.61,341.49
XS Rating Curve= 0 ,0
Exp/Cntr=0.3,0.1

Type RM Length L Ch R = 1 ,20714.8 ,219.8,223.5,226.1
XS GIS Cut Line= 2
     1980219.653      198589.753     1980199.036      198089.536
#Sta/Elev= 30
       0 2387.89    26.2 2386.16    81.8 2384.44   104.7 2382.98   160.3 2381.26
   176.7 2380.99   199.6 2379.82   209.4 2378.69   212.7 2378.56   222.5 2379.16
   238.9 2378.84     252 2379.31   261.8 2378.84   274.9 2379.45     288 2378.58
   297.8 2376.24  302.742375.739   314.1  2375.3  318.79 2375.73   320.7 2376.09
   330.5 2379.22  334.182380.021   353.4 2381.62   376.3 2382.61  384.812383.377
   402.5  2384.4   422.1 2384.77     445 2385.66   471.2 2387.78   500.6 2389.32
#Mann= 5 ,-1 , 0
       0     .12       0  302.74    .045       0  318.79     .12       0
  334.18     .06       0  384.81     .12       0
Bank Sta=302.74,318.79
XS Rating Curve= 0 ,0
Exp/Cntr=0.3,0.1

Type RM Length L Ch R = 1 ,20491.4 ,225.3,231.8,237
XS GIS Cut Line= 3
     1980409.612      198505.986     1980404.404      198403.555
     1980421.765      198222.999
#Sta/Elev= 30
       0 2396.37     9.6 2393.85    19.2 2390.86    38.5 2386.84    48.1 2384.28
    57.7 2381.92    73.7 2378.84    83.3 2377.56    86.5 2377.33   102.6 2377.53
     109 2377.31   118.8 2376.36   125.2 2375.45   138.2 2374.78   144.72373.893
   147.9 2373.79  160.822373.899   164.1 2373.98   170.6 2374.74   180.3 2375.26
   183.5 2375.68   193.3 2377.88   196.5 2378.42   212.7  2379.4   219.2 2379.95
   235.4 2380.59   251.6 2382.12   264.5 2382.57     271 2383.09     284  2383.7
#Mann= 3 ,-1 , 0
       0     .12       0   144.7    .045       0  160.82     .12       0
Bank Sta=144.7,160.82
XS Rating Curve= 0 ,0
Exp/Cntr=0.3,0.1

Type RM Length L Ch R = 1 ,20259.6 ,184.3,189.6,193.3
XS GIS Cut Line= 2
     1980550.237      198540.708     1980626.626      198323.694
#Sta/Elev= 30
       0 2397.09    16.2 2392.74    19.4 2391.63    25.9 2388.79    35.6 2385.23
    38.9 2383.82    42.1 2382.02    51.8 2375.54      68 2365.67    71.3 2364.26
    74.5 2363.89    77.8 2364.15    84.2 2365.47      94 2366.82   113.4 2369.05
   123.1 2370.75   132.8 2371.33   155.5 2371.59     162 2371.01   168.5 2372.13
   171.7 2372.03   181.5 2370.48   184.7 2370.27   197.7 2370.79   204.1 2370.71
   207.4 2371.01   217.1 2372.94   220.3  2374.2   226.8 2377.34   230.1  2378.5
#Mann= 3 ,-1 , 0
       0     .12       0      68    .045       0    84.2     .12       0
Bank Sta=68,84.2
XS Rating Curve= 0 ,0
Exp/Cntr=0.3,0.1

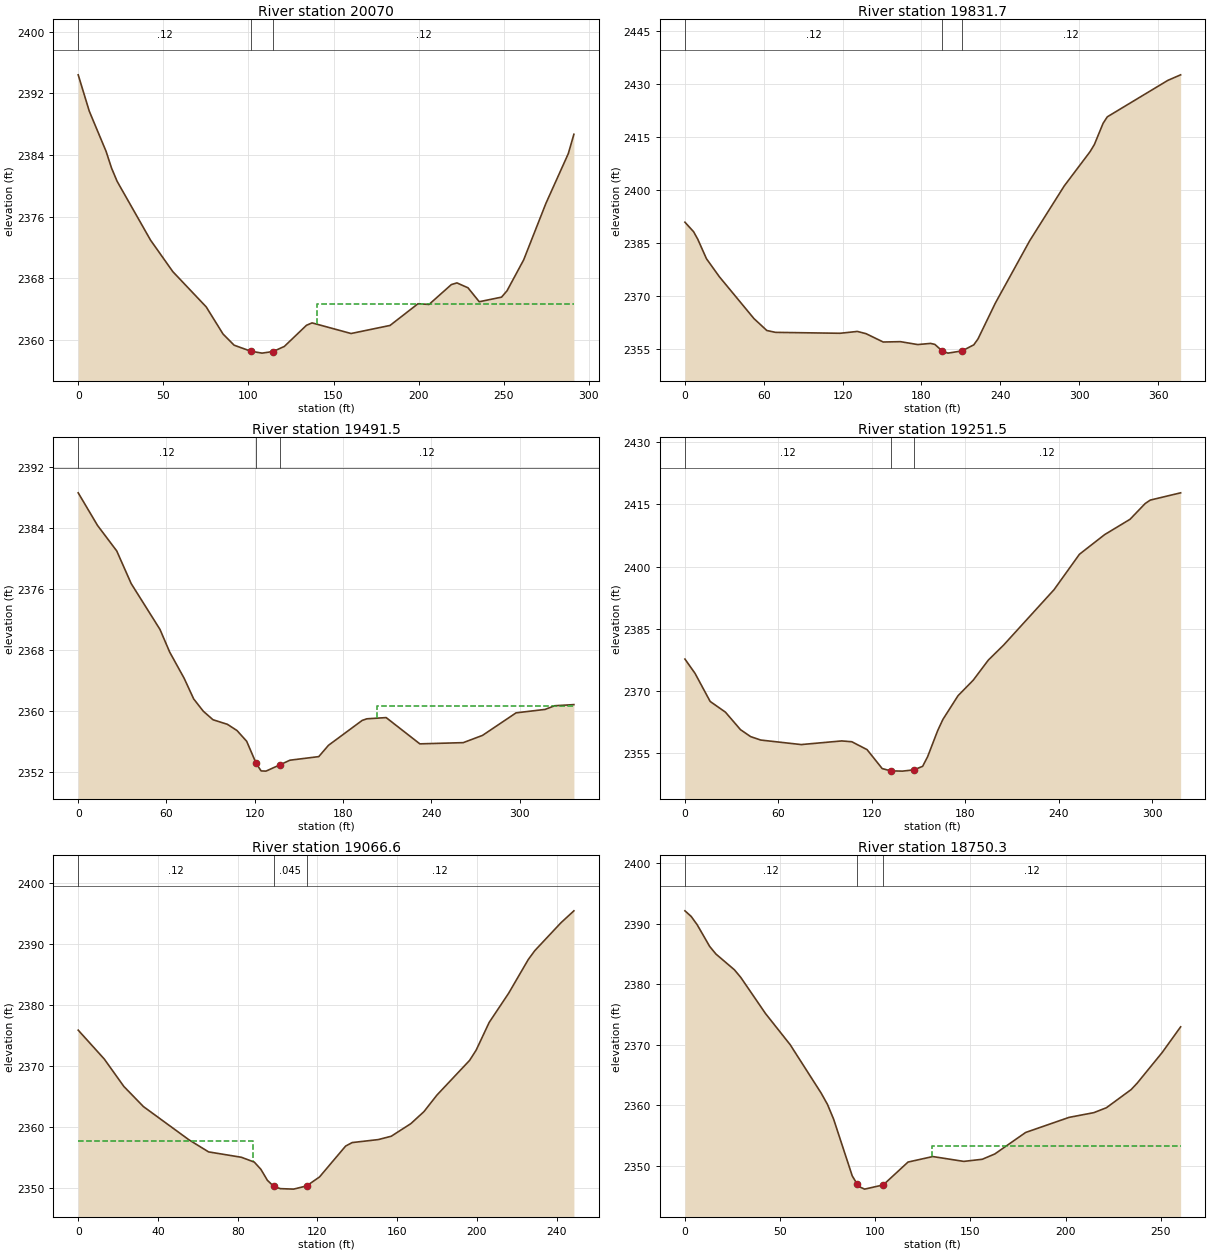
Type RM Length L Ch R = 1 ,20070   ,235.3,238.3,238.6
XS GIS Cut Line= 2
     1980692.598      198622.305     1980841.904      198372.305
#Sta/Elev= 30
       0 2394.42     6.5  2389.7    16.4 2384.46    19.6 2382.29    22.9 2380.56
    42.5 2372.93    55.6 2368.83    75.2 2364.25    85.1 2360.72    91.6 2359.27
   101.4 2358.49     108 2358.24   114.5 2358.45   121.1 2359.11   134.1 2361.86
   137.4 2362.17   160.3 2360.79   183.2 2361.84   199.6 2364.66   206.1 2364.57
   219.2 2367.15   222.5 2367.37     229 2366.73   235.6 2364.92   248.7 2365.52
   251.9 2366.34   261.7 2370.37   274.8 2377.73   287.9 2384.17   291.2 2386.69
#Mann= 3 ,-1 , 0
       0     .12       0   101.4    .045       0   114.5     .12       0
#XS Ineff= 2 , 0
                          140.56         2364.59
Permanent Ineff=
       F       F
Bank Sta=101.4,114.5
XS Rating Curve= 0 ,0
Exp/Cntr=0.3,0.1

Type RM Length L Ch R = 1 ,19831.7 ,309.8,340.2,366.8
XS GIS Cut Line= 2
     1980850.584      198769.874     1981069.334      198462.583
#Sta/Elev= 30
       0 2390.87     6.6 2388.18     9.8 2386.04    16.4 2380.54    26.2 2375.46
    52.5 2363.64    62.3 2360.27    68.9 2359.74   118.1 2359.48   131.2    2360
   137.8 2359.37   150.9 2357.01     164 2357.11   177.1 2356.29     187 2356.62
   190.2 2356.33   195.8 2354.47   200.1 2353.87   210.8 2354.49   219.8 2356.21
     223 2357.88   236.2    2368   262.4 2385.66   288.6  2401.1   308.3 2410.81
   311.6 2412.85   318.2 2418.82   321.4 2420.65   367.4 2430.94   377.2 2432.52
#Mann= 3 ,-1 , 0
       0     .12       0   195.8    .045       0   210.8     .12       0
Bank Sta=195.8,210.8
XS Rating Curve= 0 ,0
Exp/Cntr=0.3,0.1

Type RM Length L Ch R = 1 ,19491.5 ,219.2,240.1,260.1
XS GIS Cut Line= 2
      1980883.57      198811.541     1981211.695       198887.93
#Sta/Elev= 30
       0 2388.59    13.1 2384.33    26.2 2380.98      36 2376.71    55.6  2370.7
    62.2 2367.73      72 2364.31    78.5  2361.6      85    2360    91.6 2358.88
   101.4 2358.28   107.9 2357.47   114.5 2356.06     121 2353.15   124.3 2352.18
   127.6 2352.15   137.4    2353   143.9 2353.58   163.5 2354.05   170.1 2355.53
     193 2358.79   196.2    2359   209.3 2359.16   232.2 2355.72   261.7 2355.88
   274.8 2356.83   297.6 2359.78   317.3 2360.23   323.8 2360.71   336.9 2360.86
#Mann= 3 ,-1 , 0
       0     .12       0     121    .045       0   137.4     .12       0
#XS Ineff= 2 , 0
                          202.99         2360.74
Permanent Ineff=
       F       F
Bank Sta=121,137.4
XS Rating Curve= 0 ,0
Exp/Cntr=0.3,0.1

Type RM Length L Ch R = 1 ,19251.5 ,186.7,184.9,182.2
XS GIS Cut Line= 2
     1980871.418      198920.916     1981010.307      199207.374
#Sta/Elev= 30
       0 2377.73     6.5 2374.28    16.2 2367.52      26 2364.94    35.7 2360.71
    42.2 2359.04    48.7 2358.21    74.7 2357.12   100.7    2358   107.2  2357.8
     117  2355.9   126.7 2351.34   132.1 2350.79   139.7 2350.72   147.1 2351.03
   152.7 2351.88   155.9 2354.21   162.4 2360.53   165.7 2363.18   175.4 2368.89
   185.2 2372.65   194.9 2377.49   204.7  2381.1   237.1 2394.46   253.4 2402.99
   269.6 2407.73   285.9 2411.42   295.6 2415.21   298.9 2416.05   318.4  2417.8
#Mann= 3 ,-1 , 0
       0     .12       0   132.1    .045       0   147.1     .12       0
Bank Sta=132.1,147.1
XS Rating Curve= 0 ,0
Exp/Cntr=0.3,0.1

Type RM Length L Ch R = 1 ,19066.6 ,302.6,316.3,328
XS GIS Cut Line= 2
     1980711.695      199035.499     1980841.904      199247.305
#Sta/Elev= 30
       0 2375.87    13.1 2371.12    22.9 2366.63    32.7 2363.33    55.6 2357.86
    65.4 2355.89    81.8 2355.01    88.3 2354.22    91.6 2353.04    94.9 2351.22
    98.1 2350.23   101.4 2349.86     108 2349.78   114.5  2350.3     121 2351.77
   134.1 2356.84   137.4 2357.42   150.5 2357.91     157 2358.46   166.8 2360.52
   173.4  2362.5   179.9 2365.21   196.3 2370.91   199.6  2372.6   206.1 2377.13
   215.9 2381.94   225.7 2387.45     229 2388.92   242.1 2393.49   248.6 2395.45
#Mann= 3 ,-1 , 0
       0     .12       0    98.1    .045       0   114.5     .12       0
#XS Ineff= 2 , 0
           87.46 2357.74
Permanent Ineff=
       F       F
Bank Sta=98.1,114.5
XS Rating Curve= 0 ,0
Exp/Cntr=0.3,0.1

Type RM Length L Ch R = 1 ,18750.3 ,162.2,165.5,167.5
XS GIS Cut Line= 2
     1980524.195      199063.277     1980522.459      199323.694
#Sta/Elev= 30
       0  2392.1     3.3 2391.17     6.5 2389.77      13 2386.22    16.3 2384.96
      26 2382.36    29.3 2381.12    42.3 2375.15    55.3 2369.99    71.6 2361.98
    74.9 2360.12    78.1 2357.71    87.9 2348.32   90.59 2346.91    91.2 2346.59
    94.4 2346.14   104.2 2346.84   117.2 2350.61   130.2 2351.52   146.5 2350.72
   156.2 2351.07   162.8 2351.95     179  2355.5   201.8 2357.99   214.8 2358.77
   221.4 2359.58   234.4 2362.58   237.6 2363.65   250.7  2368.7   260.4 2372.94
#Mann= 3 ,-1 , 0
       0     .12       0   90.59    .045       0   104.2     .12       0
#XS Ineff= 2 , 0
                          130.03         2353.28
Permanent Ineff=
       F       F
Bank Sta=90.59,104.2
XS Rating Curve= 0 ,0
Exp/Cntr=0.3,0.1

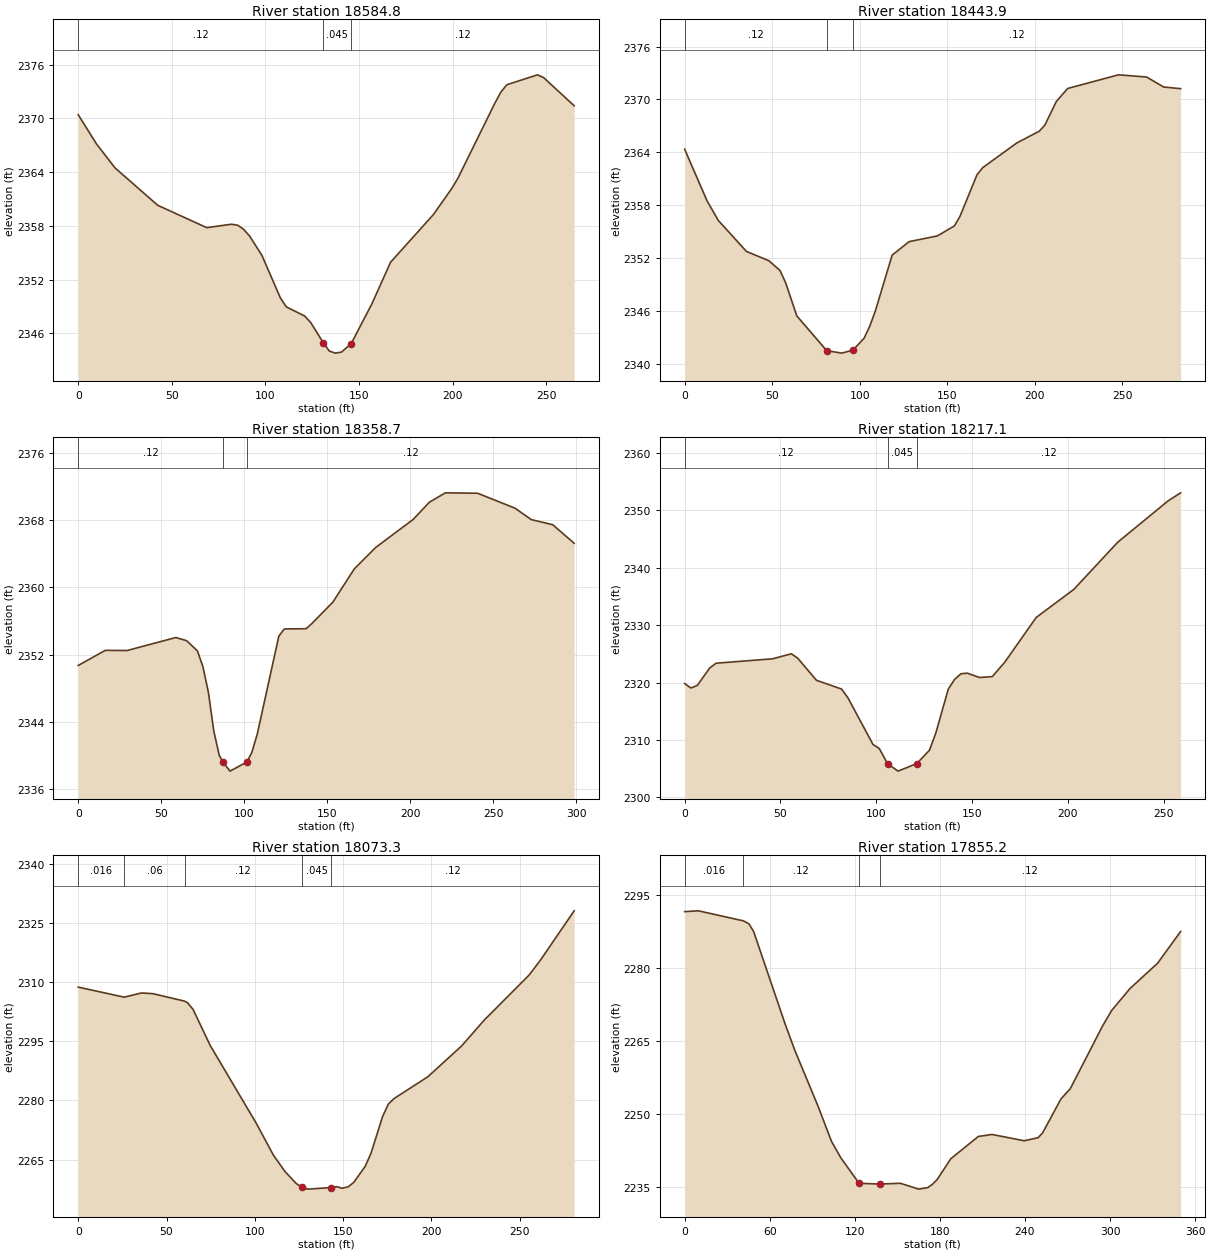
Type RM Length L Ch R = 1 ,18584.8 ,144.3,140.8,136.4
XS GIS Cut Line= 2
     1980399.237      199090.419     1980366.684       199353.44
#Sta/Elev= 30
       0  2370.4     9.8 2367.13    19.6 2364.48    42.5 2360.29    68.7  2357.8
    81.8 2358.18    85.1 2358.08    88.3 2357.63    91.6 2356.86    98.2 2354.69
     108 2349.97   111.2 2348.96   121.1 2347.93   124.3 2347.19   130.9 2344.98
   134.2 2344.03   137.4  2343.8   140.7 2343.92   145.9 2344.87     157 2349.33
   166.9 2353.94   189.8 2359.26   199.6 2362.17   202.9 2363.32   222.5 2371.63
   225.8 2372.91     229 2373.74   245.4 2374.85   248.7 2374.54     265  2371.4
#Mann= 3 , 0 , 0
       0     .12       0   130.9    .045       0   145.9     .12       0
Bank Sta=130.9,145.9
XS Rating Curve= 0 ,0
Exp/Cntr=0.3,0.1

Type RM Length L Ch R = 1 ,18443.9 ,120,85.2,48.8
XS GIS Cut Line= 3
     1980243.941      199109.965     1980249.497       199228.44
     1980361.476      199349.534
#Sta/Elev= 30
       0 2364.35    12.8  2358.5    19.2 2356.29    35.3 2352.77    48.1 2351.72
    54.5 2350.61    57.7 2349.23    64.1 2345.46    81.2 2341.52    89.8 2341.24
    96.2 2341.58   102.6 2342.94   105.8 2344.29     109 2346.02   118.6 2352.35
   128.3 2353.88   144.5 2354.53   154.2 2355.67   157.4 2356.76   167.1 2361.46
   170.4 2362.27   189.8 2365.06   202.7  2366.4   205.9 2367.09   212.4 2369.75
   218.9 2371.24     248 2372.79   264.1 2372.54   273.8 2371.41   283.5 2371.22
#Mann= 3 , 0 , 0
       0     .12       0    81.2    .045       0    96.2     .12       0
Bank Sta=81.2,96.2
XS Rating Curve= 0 ,0
Exp/Cntr=0.3,0.1

Type RM Length L Ch R = 1 ,18358.7 ,141.3,141.6,141.8
XS GIS Cut Line= 3
     1980111.997      199255.798      1980249.15       199254.93
     1980362.865      199369.514
#Sta/Elev= 30
       0  2350.7    16.3  2352.5    29.4 2352.48    58.8 2354.03    65.3 2353.65
    71.8 2352.43    75.1 2350.54    78.4 2347.48    81.6 2342.92    84.9 2340.01
   87.17 2339.17    91.4 2338.11  101.55  2339.2   104.5 2340.32   107.8 2342.51
   120.8  2354.2   124.1 2355.05   137.2 2355.08   140.4 2355.64   153.3 2358.24
   166.2  2362.2   179.1 2364.76   201.7  2368.1   211.4 2370.15   221.1 2371.27
   240.5 2371.22   263.1 2369.43   272.8 2368.08   285.7 2367.47   298.6 2365.26
#Mann= 3 , 0 , 0
       0     .12       0   87.17    .045       0  101.55     .12       0
Bank Sta=87.17,101.55
XS Rating Curve= 0 ,0
Exp/Cntr=0.3,0.1

Type RM Length L Ch R = 1 ,18217.1 ,148.9,143.8,138.1
XS GIS Cut Line= 2
     1980105.688       199396.28     1980364.578      199396.941
#Sta/Elev= 30
       0 2319.81     3.3 2319.04     6.6  2319.5    13.1 2322.54    16.4 2323.36
    45.9 2324.13    55.7    2325      59 2324.24    68.8 2320.39    81.9 2318.86
    85.2 2317.35    98.3 2309.22   101.6  2308.5  105.91 2305.86   111.4 2304.57
   121.2 2305.89   127.8 2308.22   131.1 2311.19   137.6 2318.84   140.9 2320.54
   144.2 2321.52   147.5 2321.63     154 2320.87   160.6 2321.03   167.1 2323.54
   183.5 2331.32   203.2 2336.23   226.1 2344.44   252.3 2351.61   258.9 2353.03
#Mann= 3 , 0 , 0
       0     .12       0  105.91    .045       0   121.2     .12       0
Bank Sta=105.91,121.2
XS Rating Curve= 0 ,0
Exp/Cntr=0.3,0.1

Type RM Length L Ch R = 1 ,18073.3 ,223.2,218.2,210.5
XS GIS Cut Line= 3
     1980123.154      199558.069     1980303.709      199516.402
     1980361.001      199440.013
#Sta/Elev= 30
       0  2308.7   26.082306.154    35.8 2307.22    42.3 2307.04   60.212305.151
    61.8 2304.77      65 2303.08    74.8 2293.87   100.8 2274.23   110.5 2266.16
     117 2262.04   123.5 2258.93   126.8 2258.03     130 2257.54     143 2257.93
   146.3 2258.15   149.5 2257.77   152.8 2258.11     156 2259.24   162.5 2263.32
   165.8 2266.64   172.3 2275.89   175.6 2279.08   178.8 2280.47     198 2286.01
   217.1 2293.81   229.9 2300.35   255.3 2311.76   261.7 2315.52   280.8 2328.02
#Mann= 5 ,-1 , 0
       0    .016       0   26.08     .06       0   60.21     .12       0
   126.8    .045       0     143     .12       0
Bank Sta=126.8,143
XS Rating Curve= 0 ,0
Exp/Cntr=0.3,0.1

Type RM Length L Ch R = 1 ,17855.2 ,224.9,218.5,210.9
XS GIS Cut Line= 3
     1980204.751      199795.916     1980395.723      199686.541
     1980456.487      199571.958
#Sta/Elev= 30
       0 2291.67     9.7 2291.83   41.462289.766    45.3 2289.16    48.6  2287.6
    71.2 2268.25    77.7 2263.12    93.9 2251.76   103.6 2244.37     110 2241.08
     123 2235.77   137.5 2235.61   152.1 2235.77   165.1 2234.57   171.5 2234.89
   174.8 2235.57     178 2236.51   187.7 2240.82   207.1  2245.4   216.8 2245.82
   239.5 2244.52   249.3 2245.15   252.5 2246.16   265.5 2253.17     272 2255.24
   294.6 2268.06   301.1  2271.3   314.1 2275.84   333.6 2281.06   349.8 2287.58
#Mann= 4 ,-1 , 0
       0    .016       0   41.46     .12       0     123    .045       0
   137.5     .12       0
Bank Sta=123,137.5
XS Rating Curve= 0 ,0
Exp/Cntr=0.3,0.1