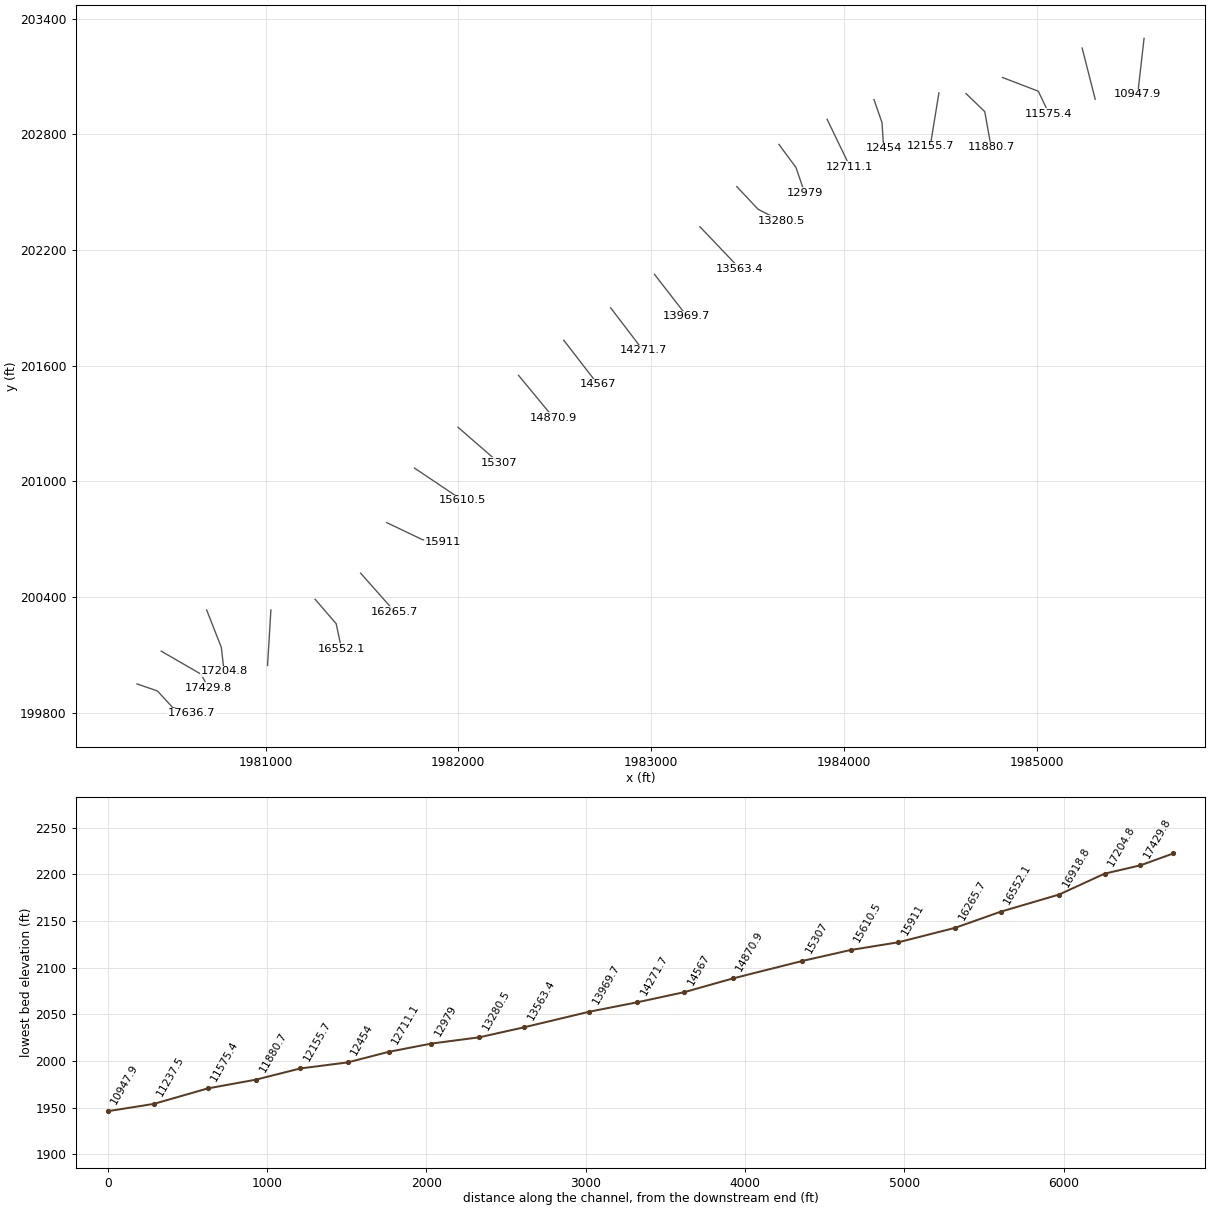
HEC-RAS study PIPESTCK.prj: PIPESTCK

--- PIPESTCK.g01 (geometry) --- (continued)

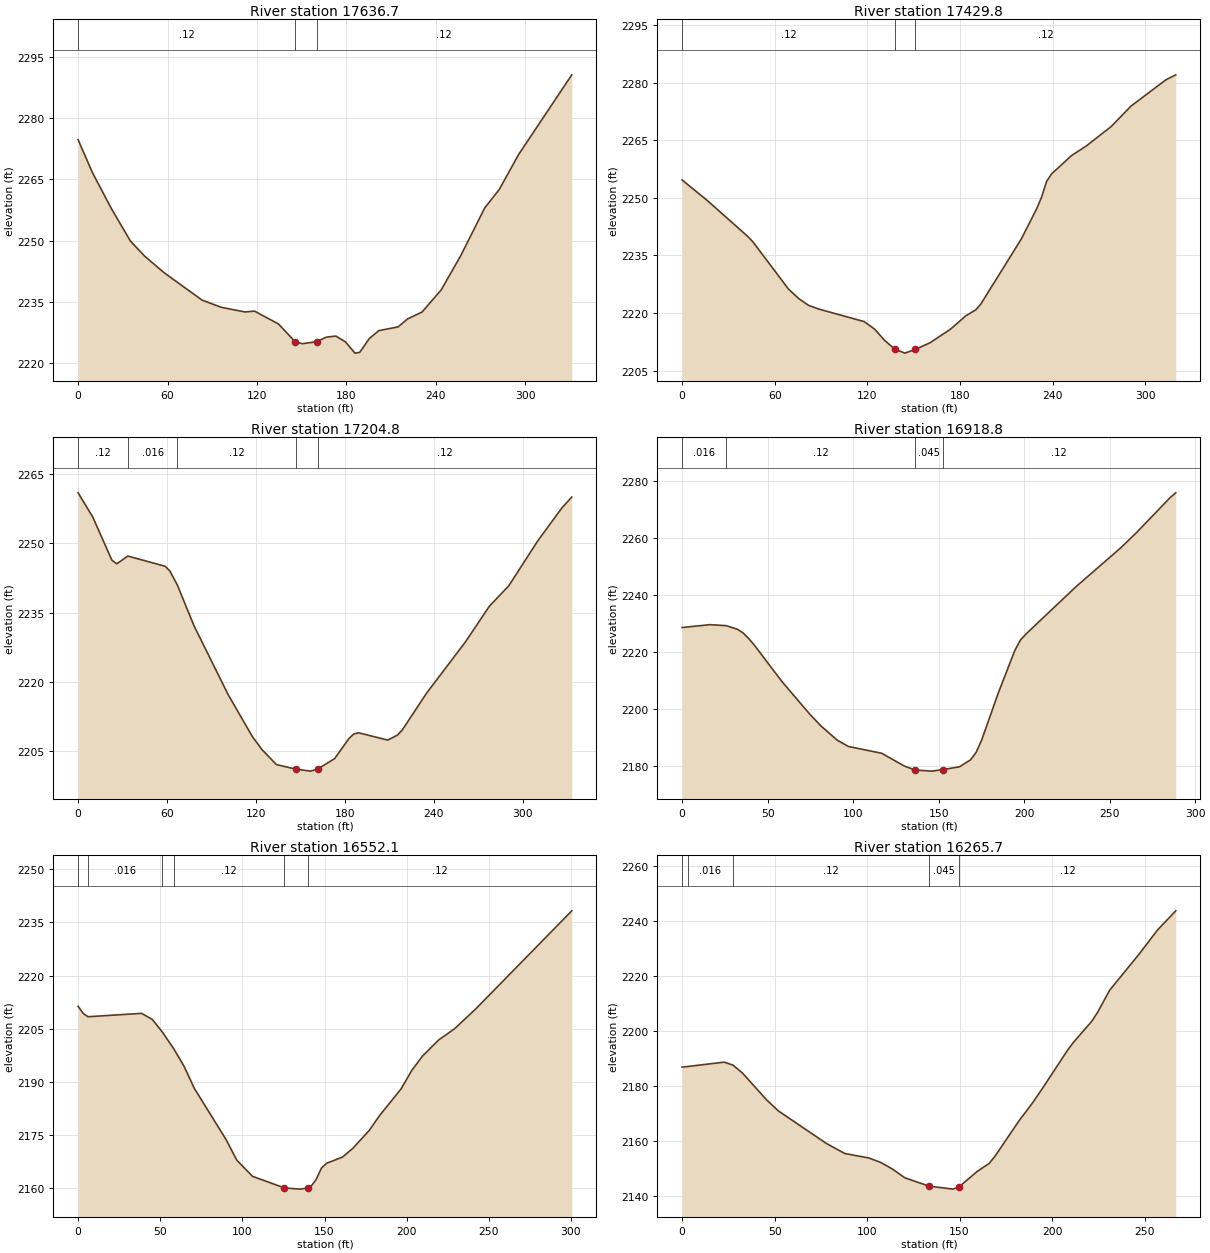
Type RM Length L Ch R = 1 ,17636.7 ,199.5,206.8,213.2
XS GIS Cut Line= 4
     1980333.223      199948.694     1980439.126      199912.236
     1980517.251      199827.166     1980616.209      199795.916
#Sta/Elev= 30
       0 2274.77     9.6 2266.71    22.4  2257.8    35.2 2249.82    44.8 2246.11
    57.6 2242.12    83.2 2235.35      96 2233.59     112 2232.44   118.4 2232.64
   134.5 2229.48   145.82225.055   150.5 2224.64   160.1 2225.12   166.5 2226.24
     173 2226.51   179.4 2225.09   185.8 2222.32     189 2222.51   195.4 2225.89
   201.8 2227.85   214.7 2228.76   221.1 2230.72   230.8 2232.42   243.7 2237.87
   256.7 2246.22   272.9 2258.02   282.6 2262.52   295.6 2271.12   331.3 2290.72
#Mann= 3 ,-1 , 0
       0     .12       0   145.8    .045       0   160.1     .12       0
Bank Sta=145.8,160.1
XS Rating Curve= 0 ,0
Exp/Cntr=0.3,0.1

Type RM Length L Ch R = 1 ,17429.8 ,239.7,225,209
XS GIS Cut Line= 3
     1980458.655      200118.745     1980665.807      199999.011
     1980703.015      199927.861
#Sta/Elev= 30
       0 2254.68    16.4  2249.3    42.6 2239.93    45.9 2238.53    68.8 2226.29
    75.4 2223.81    81.9    2222    88.5 2221.04     118 2217.76   124.6 2215.82
   131.1  2212.9   137.7 2210.59   144.2 2209.56   151.1 2210.54   160.6 2212.28
   173.7 2215.78   183.6 2219.26   190.1 2220.83   193.4 2222.35   219.6  2239.3
   229.4 2247.05   232.7 2250.17     236 2254.32   239.3  2256.3   252.1 2261.02
   261.8 2263.57   277.8  2268.6   290.6 2273.92   313.1 2280.74   319.6 2282.07
#Mann= 3 ,-1 , 0
       0     .12       0   137.7    .045       0   151.1     .12       0
Bank Sta=137.7,151.1
XS Rating Curve= 0 ,0
Exp/Cntr=0.3,0.1

Type RM Length L Ch R = 1 ,17204.8 ,295.2,286,275.4
XS GIS Cut Line= 3
     1980694.334      200332.374     1980770.723       200137.93
     1980784.612      200014.666
#Sta/Elev= 30
       0 2260.99     9.8  2255.8    22.8 2246.38    26.1  2245.6   33.57 2247.27
    58.8 2245.05      62 2243.98   66.882241.033    78.3 2232.07   101.2 2217.22
   117.5 2208.14     124  2205.3   133.8 2202.03   146.9 2201.06   156.7 2200.62
   161.72201.075     173 2203.33   182.8 2207.74   186.1 2208.71   189.3 2208.93
   208.9 2207.35   215.4 2208.43   218.7 2209.56     235 2217.51   261.1 2228.57
   277.5 2236.43   290.5 2240.82   310.1 2250.59   326.4 2257.75     333 2260.08
#Mann= 5 ,-1 , 0
       0     .12       0   33.57    .016       0   66.88     .12       0
   146.9    .045       0   161.7     .12       0
Bank Sta=146.9,161.7
XS Rating Curve= 0 ,0
Exp/Cntr=0.3,0.1

Type RM Length L Ch R = 1 ,16918.8 ,347.5,366.7,383.6
XS GIS Cut Line= 2
     1981027.668      200332.374     1981010.307       200044.18
#Sta/Elev= 30
       0 2228.63    16.2 2229.63   25.742229.284    32.4 2228.01    35.7 2226.72
    38.9  2224.8    42.2 2222.49    58.4 2209.67    74.6 2198.26    81.1 2194.14
    90.8 2189.06    97.3 2186.87   116.8 2184.48   129.8 2180.05   136.2 2178.62
     146 2178.22   152.5 2178.75   162.2 2179.73   168.7 2182.19   171.9 2184.75
   175.2 2189.15   184.9 2205.64   194.6 2220.61   197.9 2224.27   201.1 2226.34
   230.3 2242.93   256.3 2256.48     266 2262.11   285.5  2274.3   288.7 2275.91
#Mann= 4 ,-1 , 0
       0    .016       0   25.74     .12       0   136.2    .045       0
   152.5     .12       0
Bank Sta=136.2,152.5
XS Rating Curve= 0 ,0
Exp/Cntr=0.3,0.1

Type RM Length L Ch R = 1 ,16552.1 ,285.3,286.4,285.5
XS GIS Cut Line= 3
     1981256.834       200387.93     1981366.209      200261.194
     1981393.987      200130.986
#Sta/Elev= 30
       0 2211.36     3.2 2209.31    6.05 2208.41    38.6 2209.36    45.1 2207.69
   51.262204.118   58.332199.286    64.4 2194.54    70.8 2188.18    90.1 2173.76
    96.6 2167.99   106.2 2163.42   125.6 2160.16   135.2 2159.82  140.022160.164
   141.6  2160.5   144.9 2162.54   148.1 2165.74   151.3 2167.12     161 2168.86
   167.4  2171.4   177.2 2176.36   183.6 2180.61   196.6 2188.08   203.1 2193.27
   209.6 2197.29   219.4 2201.84   229.1    2205   242.1 2210.64   300.5 2238.26
#Mann= 6 ,-1 , 0
       0     .06       0    6.05    .016       0   51.26     .08       0
   58.33     .12       0   125.6    .045       0  140.02     .12       0
Bank Sta=125.6,140.02
XS Rating Curve= 0 ,0
Exp/Cntr=0.3,0.1

Type RM Length L Ch R = 1 ,16265.7 ,344.7,354.7,362.9
XS GIS Cut Line= 2
     1981492.945      200523.347     1981670.029      200323.694
#Sta/Elev= 30
       0 2186.96    3.132187.175    22.8 2188.76   27.562187.662    32.6 2184.82
    45.6 2175.09    52.1 2170.98    78.1 2159.12    87.9 2155.51   100.9 2153.88
   107.4 2152.25   113.9 2149.76   120.4 2146.66   133.4 2143.64   146.4 2142.53
   149.72143.338   159.5 2148.95     166 2151.88   169.2 2154.53   182.2 2167.46
   188.8 2173.29   195.3 2179.67   208.3 2193.01   211.5  2195.9   221.3 2203.48
   224.6 2206.83   231.1  2214.9   247.3 2228.26   257.1 2236.93   266.9 2243.84
#Mann= 5 ,-1 , 0
       0     .06       0    3.13    .016       0   27.56     .12       0
   133.4    .045       0   149.7     .12       0
Bank Sta=133.4,149.7
XS Rating Curve= 0 ,0
Exp/Cntr=0.3,0.1

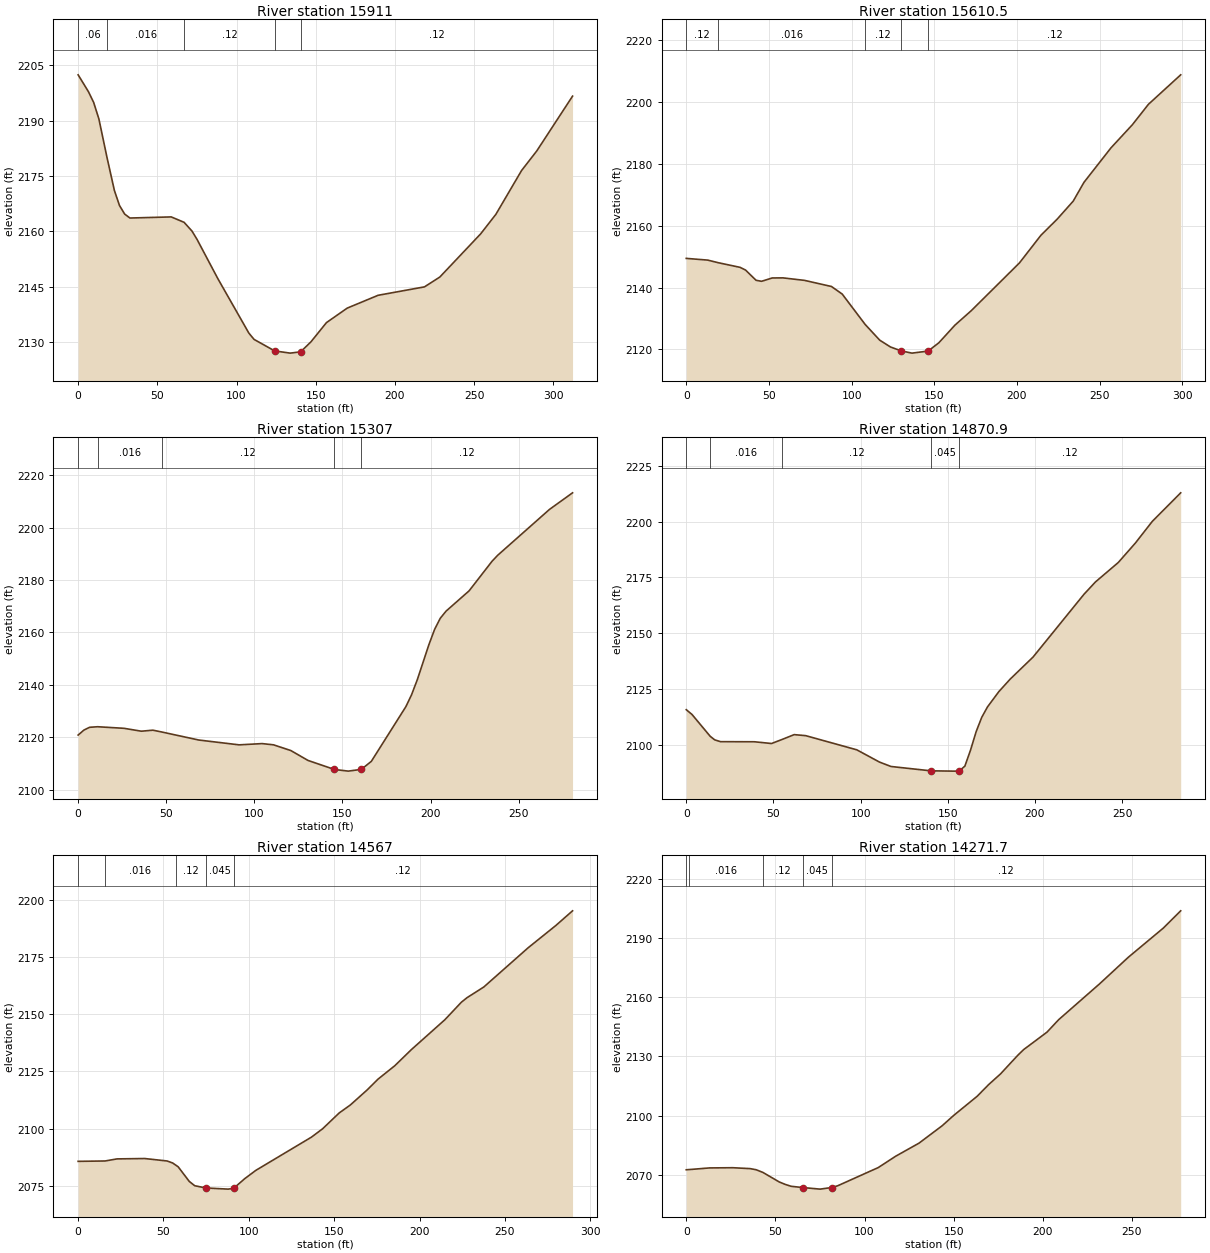
Type RM Length L Ch R = 1 ,15911   ,303.2,300.5,296.6
XS GIS Cut Line= 3
     1981628.362      200785.499     1981814.126      200696.958
     1981920.029      200686.541
#Sta/Elev= 30
       0 2202.37     6.5 2197.82     9.8 2194.91    13.1 2190.45    18.22180.073
    22.9 2171.09    26.1 2167.04    29.4  2164.7    32.7 2163.64    58.8 2163.94
    66.92162.478    71.9 2160.11    75.1 2157.85    88.2 2147.26   107.8 2132.52
   111.1 2130.81   124.1  2127.7   133.9  2127.1   140.5 2127.45     147 2130.15
   156.8 2135.35   169.9 2139.27   189.4 2142.74   218.7 2145.02   228.4 2147.68
   254.2 2159.37   263.8 2164.65     280 2176.48   289.6 2181.78   312.2  2196.6
#Mann= 5 ,-1 , 0
       0     .06       0    18.2    .016       0    66.9     .12       0
   124.1    .045       0   140.5     .12       0
Bank Sta=124.1,140.5
XS Rating Curve= 0 ,0
Exp/Cntr=0.3,0.1

Type RM Length L Ch R = 1 ,15610.5 ,305.9,303.6,300.4
XS GIS Cut Line= 2
     1981772.459      201068.486     1982020.723      200901.819
#Sta/Elev= 30
       0 2149.46      13  2148.9   19.192148.078    32.5 2146.56    35.8  2145.7
    42.2 2142.37    45.5 2142.04      52 2143.12    58.5 2143.15    71.5 2142.34
    87.8 2140.36    94.3 2137.91   108.22128.062     117 2122.98   123.5 2120.78
     130 2119.51   136.5 2118.79   146.3 2119.46   152.8 2122.17   162.5 2127.86
   172.3 2132.51   201.5    2148   214.5 2156.96   224.3 2162.16     234 2167.99
   240.5 2174.07   256.8 2185.21   269.8 2192.74   279.5 2199.34     299 2208.88
#Mann= 5 ,-1 , 0
       0     .12       0   19.19    .016       0   108.2     .12       0
     130    .045       0   146.3     .12       0
Bank Sta=130,146.3
XS Rating Curve= 0 ,0
Exp/Cntr=0.3,0.1

Type RM Length L Ch R = 1 ,15307   ,439.3,436,431.1
XS GIS Cut Line= 2
     1981998.154      201280.291     1982209.959      201096.263
#Sta/Elev= 30
       0 2120.81     3.3 2122.72     6.5 2123.77   11.052123.984    26.1 2123.38
    35.9 2122.28    42.4 2122.67   47.332121.999    68.5 2118.91    91.4 2117.07
   104.4 2117.55   110.9 2117.08   120.7  2114.9   130.5 2111.11   145.4 2107.69
   153.3 2107.04   160.72107.702   166.4 2110.77     186 2131.65   189.2 2136.14
   192.5 2141.95     199 2155.17   202.3 2161.13   205.5 2165.36   208.8 2168.11
   221.9 2175.87   234.9 2187.15   238.2 2189.49   267.5 2206.94   280.6 2213.28
#Mann= 5 ,-1 , 0
       0     .12       0   11.05    .016       0   47.33     .12       0
   145.4    .045       0   160.7     .12       0
Bank Sta=145.4,160.7
XS Rating Curve= 0 ,0
Exp/Cntr=0.3,0.1

Type RM Length L Ch R = 1 ,14870.9 ,304.3,304,302.7
XS GIS Cut Line= 2
      1982312.39      201549.388     1982492.945      201330.638
#Sta/Elev= 30
       0 2115.79     3.3 2113.64   13.732103.873    16.3  2102.3    19.6 2101.48
    39.1 2101.43    48.9 2100.65   55.162102.527    61.9 2104.63    68.5 2104.17
    97.8 2097.83   110.8 2092.35   117.4 2090.37   140.2 2088.43   153.2 2088.29
   156.5 2088.32   159.8 2090.52     163 2097.58   166.3 2106.02   169.5  2112.4
   172.8 2117.06   179.3 2123.89   185.8 2129.48   198.9 2139.34   228.2 2167.52
   234.7 2172.97   247.8 2181.68   257.6 2190.38   267.3 2200.08   283.6 2212.87
#Mann= 5 ,-1 , 0
       0     .12       0   13.73    .016       0   55.16     .12       0
   140.2    .045       0   156.5     .12       0
Bank Sta=140.2,156.5
XS Rating Curve= 0 ,0
Exp/Cntr=0.3,0.1

Type RM Length L Ch R = 1 ,14567   ,295.4,295.3,295.2
XS GIS Cut Line= 2
     1982546.765       201731.68     1982723.848      201502.513
#Sta/Elev= 30
       0 2085.75   15.812085.913    22.8 2086.82      39 2086.98    52.1 2085.91
    55.3 2085.06   57.222084.077    58.6 2083.37    65.1 2076.99    68.3 2075.11
    74.8 2074.14    87.9 2073.63    91.1    2074    97.6  2078.2   104.1 2081.82
   136.7 2096.33   143.2 2099.96   152.9 2106.86   159.4 2110.32   169.2 2116.85
   175.7 2121.65   185.5 2127.49   195.2 2134.51   214.8 2147.54   224.5  2155.2
   227.8 2157.17   237.6 2161.82   263.6 2178.95   279.8 2188.66   289.6 2195.07
#Mann= 5 ,-1 , 0
       0     .12       0   15.81    .016       0   57.22     .12       0
    74.8    .045       0    91.1     .12       0
Bank Sta=74.8,91.1
XS Rating Curve= 0 ,0
Exp/Cntr=0.3,0.1

Type RM Length L Ch R = 1 ,14271.7 ,301.1,301.9,301.8
XS GIS Cut Line= 2
      1982789.82      201900.083     1982958.223      201679.597
#Sta/Elev= 30
       0 2072.56     1.62072.662    13.1  2073.5    26.1  2073.6    35.9 2073.14
    39.2 2072.57   43.012071.212    52.2 2066.37    55.5 2065.16    58.8  2064.2
    65.3 2063.56    75.1 2062.76    81.6 2063.58    84.9 2064.44   107.7 2073.67
   117.5 2079.43   130.6 2086.06   143.6 2094.88   150.1 2100.13   163.2 2109.78
   169.7 2115.74   176.3  2121.1     186 2130.54   189.3 2133.43   202.4 2142.27
   208.9 2148.54   231.8 2166.65   248.1 2180.25   267.6 2194.92   277.4  2203.7
#Mann= 5 ,-1 , 0
       0     .12       0     1.6    .016       0   43.01     .12       0
    65.3    .045       0    81.6     .12       0
Bank Sta=65.3,81.6
XS Rating Curve= 0 ,0
Exp/Cntr=0.3,0.1

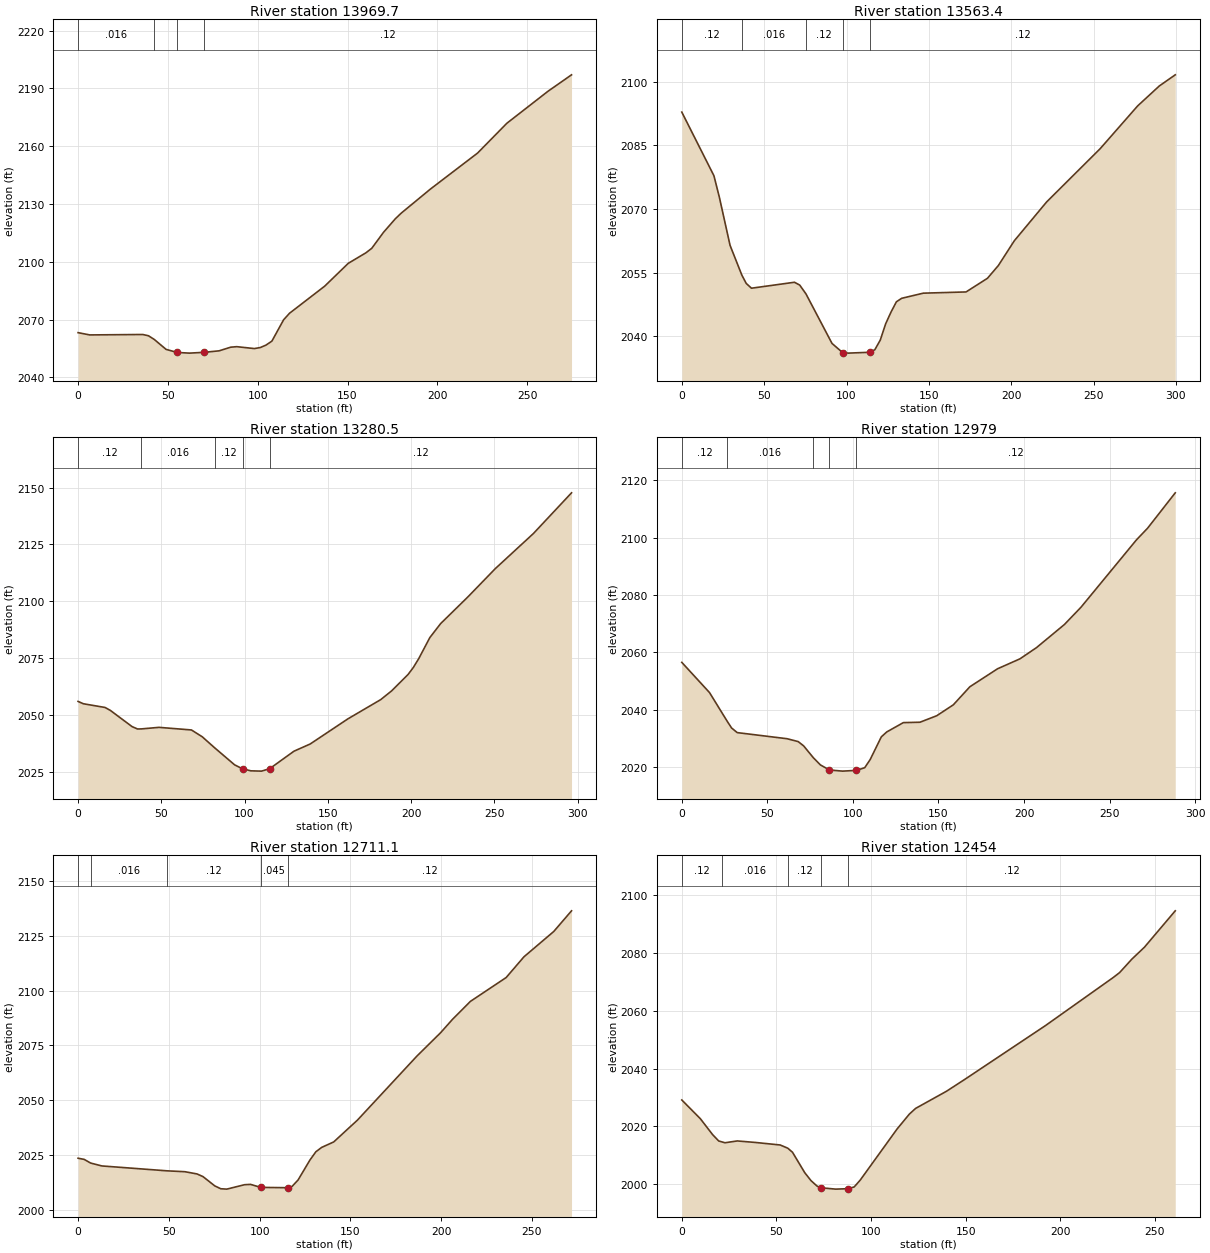
Type RM Length L Ch R = 1 ,13969.7 ,402.4,406.3,408
XS GIS Cut Line= 2
     1983017.251      202073.694     1983185.654       201856.68
#Sta/Elev= 30
       0 2063.24     6.5 2062.07      36 2062.29    39.2 2061.63   42.442059.696
      49 2054.56    55.2 2052.96    62.1 2052.62    70.2 2053.04    78.5 2053.81
      85 2055.71    88.3 2055.97    98.1 2054.99   101.4 2055.51   104.6 2056.78
   107.9 2058.86   114.4  2069.9   117.7 2073.31   137.3 2087.39   150.4 2099.22
   160.2 2104.67   163.5 2107.03     170 2115.29   176.6 2122.34   179.9 2125.29
   196.2 2137.81   222.4 2156.46   238.7 2171.93   261.6 2188.54   274.7 2197.07
#Mann= 4 ,-1 , 0
       0    .016       0   42.44     .12       0    55.2    .045       0
    70.2     .12       0
Bank Sta=55.2,70.2
XS Rating Curve= 0 ,0
Exp/Cntr=0.3,0.1

Type RM Length L Ch R = 1 ,13563.4 ,282.8,282.9,282.4
XS GIS Cut Line= 2
     1983253.362      202320.222     1983459.959      202103.208
#Sta/Elev= 30
       0  2092.8    19.5 2077.82    22.8 2072.76    29.3 2061.42   36.482054.397
    39.1 2052.46    42.3 2051.33    68.4 2052.73    71.6 2052.06   75.382049.997
    91.2 2038.32    97.7 2036.15     101 2036.04     114 2036.24   117.2 2036.84
   120.5 2039.11   123.8 2042.97     127 2045.69   130.3 2048.13   133.5 2048.95
   146.6 2050.16   172.6 2050.45   185.6 2053.67   192.2 2056.67   201.9 2062.51
   221.5 2071.64     254 2084.18   276.8 2094.27   289.9 2098.95   299.6 2101.58
#Mann= 5 ,-1 , 0
       0     .12       0   36.48    .016       0   75.38     .12       0
    97.7    .045       0     114     .12       0
Bank Sta=97.7,114
XS Rating Curve= 0 ,0
Exp/Cntr=0.3,0.1

Type RM Length L Ch R = 1 ,13280.5 ,303.8,301.5,298.5
XS GIS Cut Line= 3
     1983444.334      202528.555     1983555.445      202410.499
     1983675.237      202349.736
#Sta/Elev= 30
       0 2055.91     3.2 2054.88    16.2 2053.25    19.4 2051.95    32.4 2044.84
    35.7 2043.78      382043.816    48.6  2044.5    68.1 2043.35    74.6 2040.34
   82.032035.502      94 2028.02   98.942026.201   103.8 2025.37   110.2 2025.24
  115.082026.313   129.7 2034.02   139.4 2037.17   162.1 2048.25   181.8 2056.71
   188.3 2060.53   198.2 2067.75   201.4 2070.87   204.7 2074.84   211.3 2084.01
   217.8 2090.17   234.2 2101.93   250.6 2114.33   273.5 2129.78   296.4 2147.69
#Mann= 5 ,-1 , 0
       0     .12       0      38    .016       0   82.03     .12       0
   98.94    .045       0  115.08     .12       0
Bank Sta=98.94,115.08
XS Rating Curve= 0 ,0
Exp/Cntr=0.3,0.1

Type RM Length L Ch R = 1 ,12979   ,271.7,267.9,263.3
XS GIS Cut Line= 3
     1983663.084      202747.305     1983751.626      202627.513
     1983796.765      202495.569
#Sta/Elev= 30
       0 2056.45    16.2 2045.91   26.592035.848    29.1 2033.55    32.4 2031.94
    61.5 2029.81      68 2028.81    71.2 2027.32   76.832023.209      81 2020.67
   86.282018.905    93.9  2018.5  102.022018.751   106.9 2019.69   110.1 2022.54
   116.6 2030.45   119.8 2032.18   129.5 2035.43   139.2 2035.56     149 2037.83
   158.7 2041.64   168.4 2047.96   184.6 2054.23   197.6 2057.67   207.3 2061.59
   223.6 2069.65   233.3 2075.68   265.7 2099.18   272.2 2103.24   288.4 2115.61
#Mann= 5 ,-1 , 0
       0     .12       0   26.59    .016       0   76.83     .12       0
   86.28    .045       0  102.02     .12       0
Bank Sta=86.28,102.02
XS Rating Curve= 0 ,0
Exp/Cntr=0.3,0.1

Type RM Length L Ch R = 1 ,12711.1 ,259.6,257.1,254.5
XS GIS Cut Line= 2
     1983913.084      202877.513      1984031.14      202632.722
#Sta/Elev= 30
       0 2023.69     3.3 2023.18    6.912021.497    13.1 2020.18   49.022017.953
    58.9 2017.55    65.5 2016.54    68.8 2015.33    75.3  2011.1    78.6  2009.8
    81.9 2009.63    91.7 2011.64      95 2011.79   100.6 2010.42   115.6 2010.27
   117.9 2010.89   121.2 2013.82   127.7 2022.86     131 2026.65   134.2 2028.63
   140.8  2031.1   153.9 2041.05   186.6 2070.14   199.7 2080.82   206.3 2086.94
   216.1 2095.06   235.8 2105.92   245.6 2115.35     262 2126.86   271.8 2136.27
#Mann= 5 ,-1 , 0
       0     .12       0    6.91    .016       0   49.02     .12       0
   100.6    .045       0   115.6     .12       0
Bank Sta=100.6,115.6
XS Rating Curve= 0 ,0
Exp/Cntr=0.3,0.1

Type RM Length L Ch R = 1 ,12454   ,309.5,298.3,287.1
XS GIS Cut Line= 3
      1984156.14      202979.944     1984197.807      202860.152
     1984206.487      202726.472
#Sta/Elev= 30
       0 2029.15     9.8 2022.68    16.3 2017.16    19.5 2014.98   21.052014.689
    22.8 2014.36    29.3 2014.99      39 2014.46      52 2013.59   56.012012.481
    58.5 2011.08      65    2004    68.3 2001.26    71.6 1999.32   73.821998.786
    81.3 1998.33    87.8 1998.48    91.1 1999.08    94.3 2001.45   113.8 2019.14
   120.3 2024.29   123.6 2026.25   139.9 2032.17   149.7 2036.33   192.2 2054.87
   228.1 2071.53   231.4  2073.2   237.9 2077.87   244.5 2081.96   260.8 2094.55
#Mann= 5 ,-1 , 0
       0     .12       0   21.05    .016       0   56.01     .12       0
   73.82    .045       0    87.8     .12       0
Bank Sta=73.82,87.8
XS Rating Curve= 0 ,0
Exp/Cntr=0.3,0.1

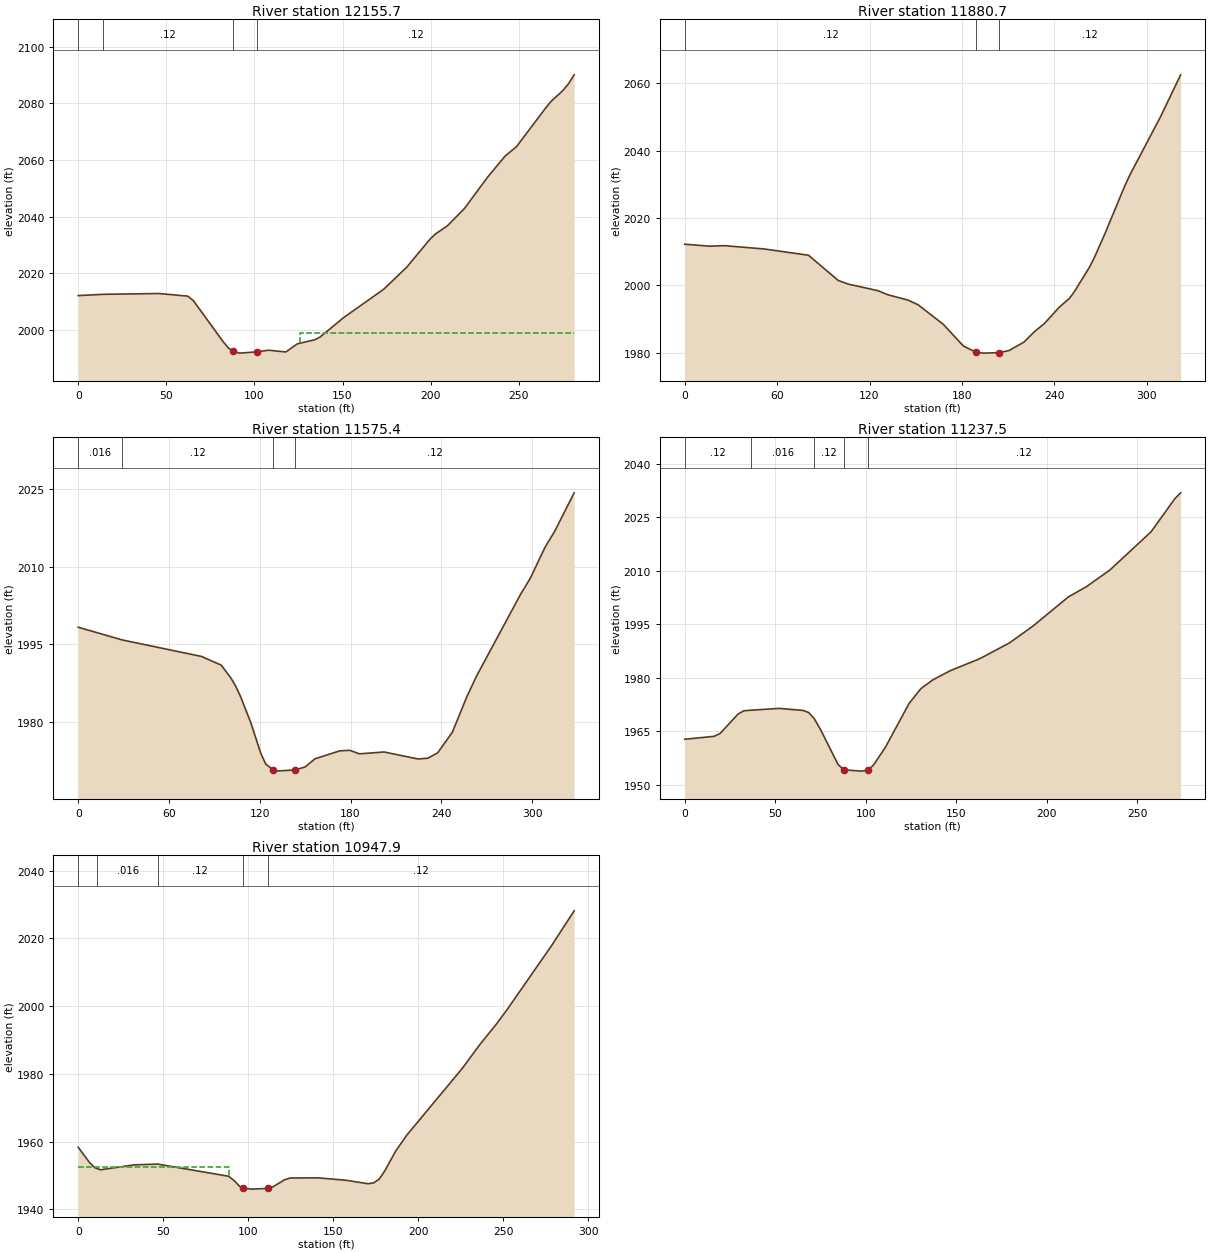
Type RM Length L Ch R = 1 ,12155.7 ,267,275.1,282.4
XS GIS Cut Line= 2
     1984492.945      203014.666     1984447.807      202736.888
#Sta/Elev= 30
       0 2012.12   14.312012.577    45.8 2012.86    62.2 2011.93    65.4  2010.3
    81.8 1996.23    85.1 1993.69   87.641992.558    91.6 1991.82   101.4 1992.27
     108 1992.85   117.8 1992.23   124.4 1995.11   134.2 1996.53   137.4 1997.58
   150.5 2004.31   173.4  2014.4   186.5 2022.21   199.6 2032.03   202.9 2033.96
   209.4  2036.7   219.2  2042.9   232.3 2053.94   242.2 2061.35   248.7  2064.7
   265.1 2078.24   268.3 2080.67   274.9 2084.43   278.2 2086.87   281.4 2090.04
#Mann= 4 ,-1 , 0
       0    .016       0   14.31     .12       0   87.64    .045       0
   101.4     .12       0
#XS Ineff= 2 , 0
                           125.7         1999.05
Permanent Ineff=
       F       F
Bank Sta=87.64,101.4
XS Rating Curve= 0 ,0
Exp/Cntr=0.3,0.1

Type RM Length L Ch R = 1 ,11880.7 ,281.6,305.3,328.2
XS GIS Cut Line= 3
      1984633.57      203011.194     1984730.793      202917.444
     1984763.779      202733.416
#Sta/Elev= 30
       0 2012.23    16.1 2011.64    25.7  2011.8    51.4 2010.83    80.4 2008.96
    99.7 2001.48   106.1 2000.41   125.4 1998.46   131.8 1997.26   144.9 1995.67
   151.5 1994.29   167.9 1988.48     181 1982.03  189.271980.186   194.1 1979.93
   203.9 1980.07   210.5 1980.68   220.3  1983.2   226.9 1986.22   233.5 1988.68
   243.3  1993.6   249.9  1996.2   253.1 1998.21     263 2005.55   266.3 2008.57
   272.8 2015.29   285.9 2029.68   289.2  2032.9   308.9 2049.97     322 2062.46
#Mann= 3 ,-1 , 0
       0     .12       0  189.27    .045       0   203.9     .12       0
Bank Sta=189.27,203.9
XS Rating Curve= 0 ,0
Exp/Cntr=0.3,0.1

Type RM Length L Ch R = 1 ,11575.4 ,359.2,337.9,315.3
XS GIS Cut Line= 3
     1984822.807      203094.527      1985008.57      203023.347
     1985064.126      202907.027
#Sta/Elev= 30
       0 1998.29   29.131995.823    81.5 1992.63    94.6 1990.93   101.1 1988.37
   104.4  1986.7   107.6 1984.65   114.1 1979.78   120.7 1973.84   123.9 1971.81
   128.7 1970.67   130.4 1970.41   143.5 1970.65     150 1971.22   156.5  1972.8
   172.8 1974.33   179.4 1974.45   185.9 1973.76   202.2 1974.12   224.7 1972.76
   231.2 1972.92   237.6 1973.96   247.3 1977.95   256.9 1984.85   263.4 1988.89
   292.4 2004.68   298.8 2007.77   308.5 2013.75     315 2016.91   327.8 2024.33
#Mann= 4 ,-1 , 0
       0    .016       0   29.13     .12       0   128.7    .045       0
   143.5     .12       0
Bank Sta=128.7,143.5
XS Rating Curve= 0 ,0
Exp/Cntr=0.3,0.1

Type RM Length L Ch R = 1 ,11237.5 ,297.5,289.6,281.2
XS GIS Cut Line= 2
     1985236.001      203247.305     1985303.709       202981.68
#Sta/Elev= 30
       0  1962.8    16.3 1963.62    19.6 1964.42    29.4 1969.81    32.6 1970.76
   36.661970.938    52.2 1971.44    65.3 1970.89    68.5  1970.3   71.561968.612
    75.1 1965.51    84.8  1955.7    88.1 1954.22    97.9 1953.87   101.2 1954.13
   104.4  1955.6     111 1960.61     124  1972.8   130.5 1976.95   137.1 1979.42
   146.8 1982.01   163.2 1985.39   179.5 1989.79   192.5  1994.5   212.1 2002.69
   221.9 2005.49     235  2010.2   257.8 2020.93   270.9 2030.18   274.1 2031.83
#Mann= 5 ,-1 , 0
       0     .12       0   36.66    .016       0   71.56     .12       0
    88.1    .045       0   101.2     .12       0
Bank Sta=88.1,101.2
XS Rating Curve= 0 ,0
Exp/Cntr=0.3,0.1

Type RM Length L Ch R = 1 ,10947.9 ,299.1,329.8,359.2
XS GIS Cut Line= 2
     1985557.182      203297.652     1985524.195      203007.722
#Sta/Elev= 30
       0 1958.36     6.6  1953.9     9.8 1952.32   11.331952.037    13.1 1951.71
    32.8 1953.16   46.681953.395    88.5  1949.8    91.8 1948.49    95.1 1946.78
   97.071946.339   101.6    1946   111.5  1946.2   114.8 1946.74   121.3 1948.74
   124.6 1949.28     141 1949.33   157.4 1948.63   170.5  1947.6   173.8 1947.84
     177  1948.9   180.3 1951.31   186.9 1957.32   193.4 1961.98   226.2 1981.78
   236.1 1988.55   245.9 1994.63   252.5  1999.1   278.7 2018.02   291.8 2028.16
#Mann= 5 ,-1 , 0
       0     .12       0   11.33    .016       0   46.68     .12       0
   97.07    .045       0   111.5     .12       0
#XS Ineff= 2 , 0
           88.85 1952.67
Permanent Ineff=
       F       F
Bank Sta=97.07,111.5
XS Rating Curve= 0 ,0
Exp/Cntr=0.3,0.1