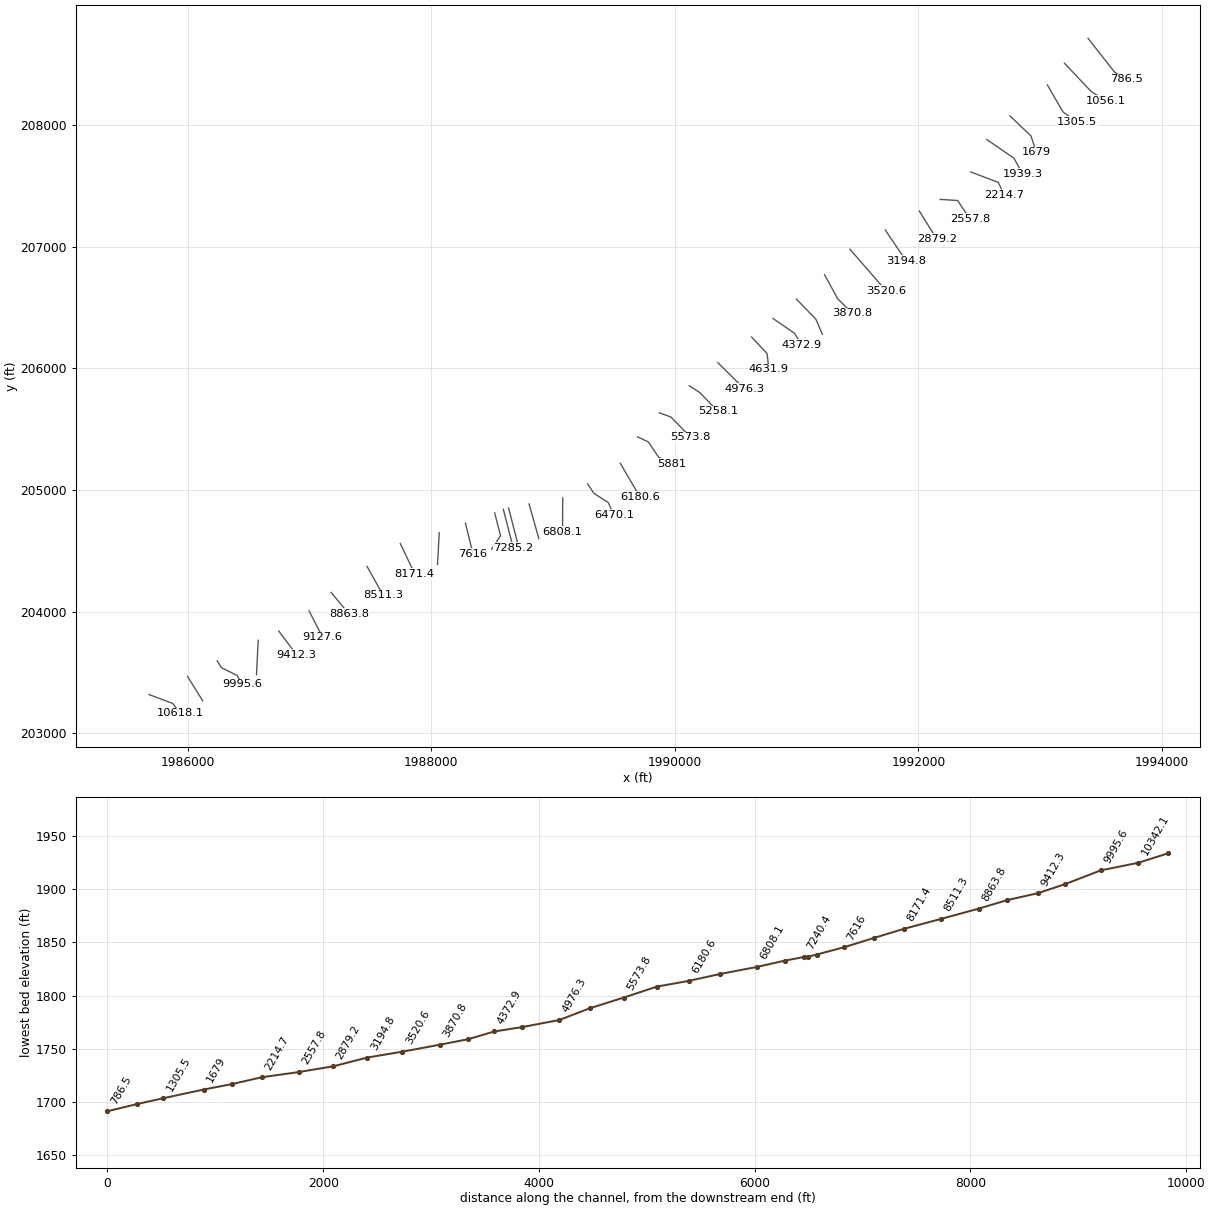
HEC-RAS study PIPESTCK.prj: PIPESTCK

--- PIPESTCK.g01 (geometry) --- (continued)

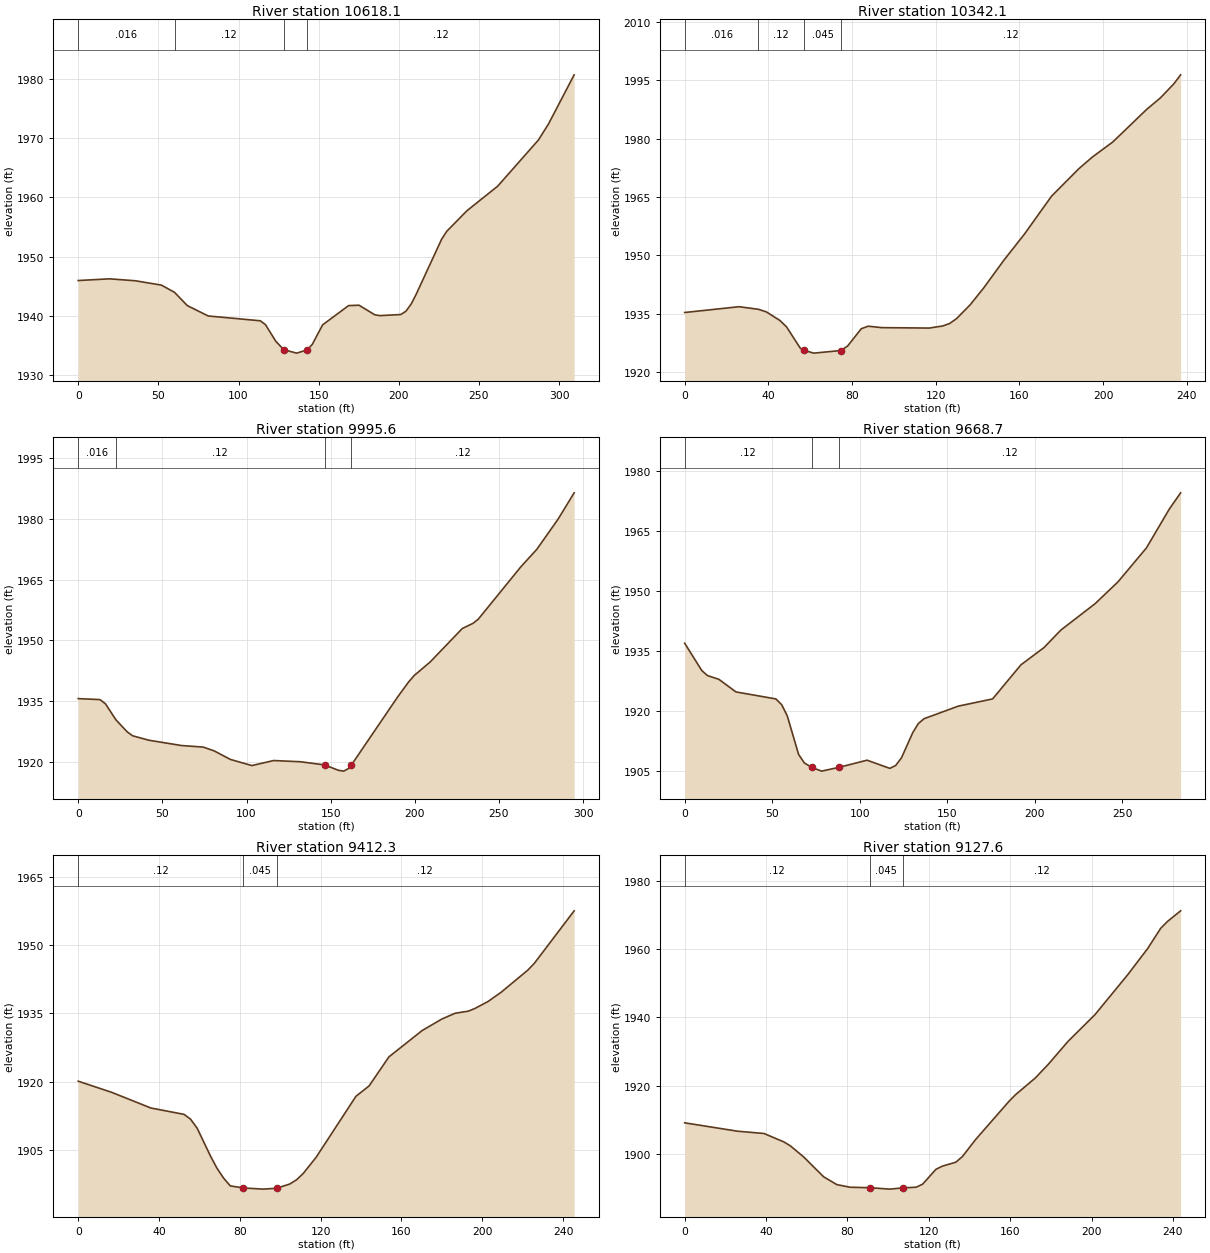
Type RM Length L Ch R = 1 ,10618.1 ,291.1,276,261.1
XS GIS Cut Line= 3
     1985683.918      203316.749     1985878.362      203243.833
     1985939.126      203162.236
#Sta/Elev= 30
       0 1945.96    19.5 1946.25    35.7 1945.92    51.9 1945.19    60.11943.969
    68.1 1941.73    81.1 1939.99   113.6 1939.18   116.8 1938.54   123.3 1935.72
  128.281934.297   136.3 1933.73   142.8 1934.27     146 1935.19   152.5  1938.5
   168.7 1941.74   175.2  1941.8     185 1940.19   188.2 1940.05   201.2 1940.23
   204.4 1940.78   207.7 1941.99   210.8 1943.62   226.7 1952.91   229.9 1954.25
   242.6 1957.74   261.7 1961.86   287.2 1969.67   293.5 1972.39   309.4 1980.62
#Mann= 4 ,-1 , 0
       0    .016       0    60.1     .12       0  128.28    .045       0
   142.8     .12       0
Bank Sta=128.28,142.8
XS Rating Curve= 0 ,0
Exp/Cntr=0.3,0.1

Type RM Length L Ch R = 1 ,10342.1 ,332.2,346.5,358.8
XS GIS Cut Line= 2
      1985999.89      203466.055      1986124.89      203264.666
#Sta/Elev= 30
       0 1935.31      26  1936.8   35.211936.137      39 1935.48    45.5 1933.27
    48.7 1931.61    55.2 1926.17   57.051925.578    61.7 1924.87    74.7 1925.54
    77.9 1926.72    84.4 1931.14    87.7 1931.79    94.2 1931.42   116.9 1931.31
   123.4 1931.86   126.6 1932.48   129.9 1933.73   136.4 1937.27   142.9 1941.63
   152.6 1948.79   162.4 1955.48   175.3 1965.19   188.3 1972.23   194.8 1975.25
   204.6 1979.14   220.8 1987.52   227.3 1990.44   233.8  1994.1     237 1996.39
#Mann= 4 ,-1 , 0
       0    .016       0   35.21     .12       0   57.05    .045       0
    74.7     .12       0
Bank Sta=57.05,74.7
XS Rating Curve= 0 ,0
Exp/Cntr=0.3,0.1

Type RM Length L Ch R = 1 ,9995.6  ,352.9,326.9,299
XS GIS Cut Line= 4
     1986242.945      203594.527     1986279.404      203537.236
      1986406.14      203474.736     1986447.807      203400.083
#Sta/Elev= 30
       0 1935.65    12.9 1935.41    16.2 1934.38   22.431930.414    29.1 1927.46
    32.3 1926.49      42 1925.39    61.4 1924.08    74.3  1923.7    80.8 1922.76
    90.4 1920.66   103.2 1919.14   116.1 1920.38   132.1 1920.08  146.511919.294
   154.6 1917.98   157.8 1917.77     161  1918.5  162.211919.206     190 1936.17
   196.4 1939.79   199.6 1941.33   209.2 1944.71   228.2 1952.93   234.6 1954.22
   237.7 1955.23     263 1968.14   272.6 1972.51   285.2 1979.94   294.7  1986.4
#Mann= 4 ,-1 , 0
       0    .016       0   22.43     .12       0  146.51    .045       0
  162.21     .12       0
Bank Sta=146.51,162.21
XS Rating Curve= 0 ,0
Exp/Cntr=0.3,0.1

Type RM Length L Ch R = 1 ,9668.7  ,240.2,256.4,271.7
XS GIS Cut Line= 2
     1986579.751       203762.93     1986565.862      203479.944
#Sta/Elev= 30
       0 1936.92     9.8 1930.08      13 1928.84    19.5 1927.91    29.3 1924.75
    52.1    1923    55.4 1921.57    58.6 1918.77    65.1 1909.11    68.4 1906.99
   72.541905.905    78.2 1904.96    87.9 1905.88   104.2 1907.69   117.2 1905.65
   120.5 1906.36   123.8 1908.24   130.3 1914.59   133.5 1916.86   136.8 1918.07
   156.3  1921.2   175.9    1923   192.1 1931.53   205.2 1935.81   214.9 1940.21
   234.5 1946.82   247.5 1952.24   263.8 1960.75   276.8 1970.41   283.3  1974.5
#Mann= 3 ,-1 , 0
       0     .12       0   72.54    .045       0    87.9     .12       0
Bank Sta=72.54,87.9
XS Rating Curve= 0 ,0
Exp/Cntr=0.3,0.1

Type RM Length L Ch R = 1 ,9412.3  ,288.4,284.7,280.7
XS GIS Cut Line= 2
     1986748.154      203839.319     1986895.723      203643.138
#Sta/Elev= 30
       0 1920.07    16.4 1917.64      36 1914.16    52.4 1912.76    55.6 1911.71
    58.9  1909.7    65.5 1903.56    68.7 1900.89      72  1898.7    75.3    1897
    81.8 1896.55    91.6 1896.29    98.2 1896.48   104.7 1897.41     108 1898.32
   111.3 1899.69   117.8 1903.32   137.5 1916.75     144 1919.03   153.8 1925.42
   170.2 1931.21     180 1933.76   186.6 1935.04   193.1 1935.49   196.4 1936.09
   202.9 1937.63   209.5 1939.71   222.6 1944.55   225.8 1946.04   245.5  1957.6
#Mann= 3 ,-1 , 0
       0     .12       0    81.8    .045       0    98.2     .12       0
Bank Sta=81.8,98.2
XS Rating Curve= 0 ,0
Exp/Cntr=0.3,0.1

Type RM Length L Ch R = 1 ,9127.6  ,258.8,263.8,268.6
XS GIS Cut Line= 2
     1986998.154      204004.249     1987109.265      203787.236
#Sta/Elev= 30
       0 1909.17      26 1906.72      39 1906.05    48.8 1903.58      52 1902.42
    58.5 1899.19    68.3 1893.39    74.8  1891.1    81.3 1890.33      91  1890.2
   100.8 1889.78   107.31890.146   113.8 1890.34     117 1891.24   123.5 1895.57
   126.8 1896.53   133.3 1897.65   136.5 1899.29     143 1904.27   159.3 1915.37
   162.5 1917.32   172.3 1922.25   178.8 1926.32   188.5 1933.03   201.6 1940.74
   217.8 1952.48   227.6 1960.14     234 1966.05   237.3 1968.04   243.8 1971.17
#Mann= 3 ,-1 , 0
       0     .12       0      91    .045       0   107.3     .12       0
Bank Sta=91,107.3
XS Rating Curve= 0 ,0
Exp/Cntr=0.3,0.1

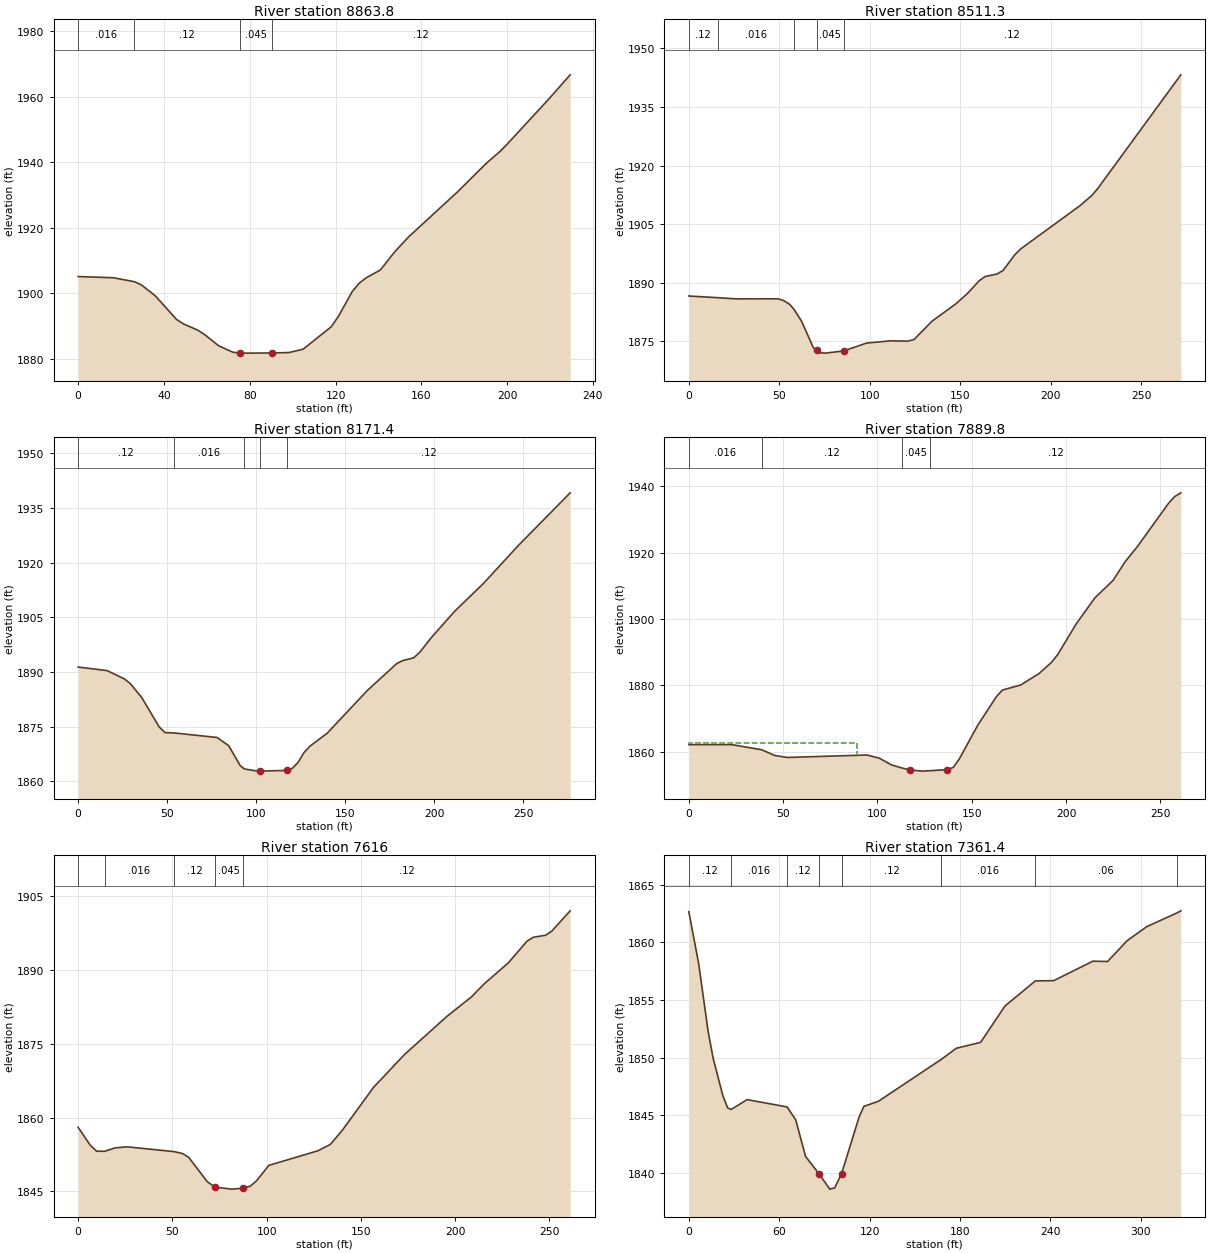
Type RM Length L Ch R = 1 ,8863.8  ,356.3,352.5,348.1
XS GIS Cut Line= 2
     1987178.709      204157.027     1987324.543      203979.944
#Sta/Elev= 30
       0 1905.15    16.4 1904.78   26.271903.569    29.5  1902.6      36 1899.24
    45.9 1892.04    49.2 1890.66    55.7 1888.81      59 1887.42    65.5 1884.02
    72.1 1882.06    75.4 1881.81    78.6 1881.77    90.4 1881.82    98.3 1881.95
   104.9 1882.97     118 1889.81   121.3 1892.93   127.8 1900.56   131.1 1903.16
   134.4  1904.8   140.9 1907.15   147.5 1912.61     154  1917.2     177 1931.06
   190.1 1939.58   196.6 1943.28   199.9 1945.47   219.6 1959.45   229.4 1966.72
#Mann= 4 ,-1 , 0
       0    .016       0   26.27     .12       0    75.4    .045       0
    90.4     .12       0
Bank Sta=75.4,90.4
XS Rating Curve= 0 ,0
Exp/Cntr=0.3,0.1

Type RM Length L Ch R = 1 ,8511.3  ,340.6,339.9,337.8
XS GIS Cut Line= 2
     1987473.848      204370.569     1987605.793      204132.722
#Sta/Elev= 30
       0 1886.63   16.051886.197    26.2  1885.9    49.2 1885.91    52.4 1885.48
    55.7 1884.52   58.141883.248    62.3 1880.22    68.8 1873.46    70.6 1872.74
    72.1 1872.14    75.4 1872.02    85.6 1872.58    98.3 1874.59   111.4 1875.16
   121.2 1875.09   124.5  1875.5   134.4 1880.16   147.5 1884.58     154 1887.25
   160.6 1890.56   163.8 1891.61   170.4 1892.26   173.7 1893.14   180.2 1897.16
   183.5 1898.68   216.3 1909.75   222.8 1912.34   226.1 1914.13     272  1943.2
#Mann= 5 ,-1 , 0
       0     .12       0   16.05    .016       0   58.14     .12       0
    70.6    .045       0    85.6     .12       0
Bank Sta=70.6,85.6
XS Rating Curve= 0 ,0
Exp/Cntr=0.3,0.1

Type RM Length L Ch R = 1 ,8171.4  ,292.5,281.6,270.2
XS GIS Cut Line= 2
     1987746.418      204559.805     1987864.473      204309.805
#Sta/Elev= 30
       0 1891.36    16.3 1890.38      26  1888.1    29.3 1886.81    35.8 1882.96
    45.5 1874.96    48.8 1873.37   54.151873.266    78.1 1872.03    84.6 1869.78
    91.1  1864.3   93.471863.382   100.8  1862.8   102.3 1862.81   117.3 1862.99
   120.4 1863.57   123.6 1865.19   126.8  1867.8   130.1 1869.58   139.9 1873.18
   162.6 1884.96   178.9 1892.25   182.2 1893.09   188.6  1893.9   191.9 1895.36
   198.4 1899.39   211.4 1906.57   227.7 1914.25   247.2 1924.61   276.5 1939.16
#Mann= 5 ,-1 , 0
       0     .12       0   54.15    .016       0   93.47     .12       0
   102.3    .045       0   117.3     .12       0
Bank Sta=102.3,117.3
XS Rating Curve= 0 ,0
Exp/Cntr=0.3,0.1

Type RM Length L Ch R = 1 ,7889.8  ,266.6,273.8,279.8
XS GIS Cut Line= 2
     1988065.862      204648.347     1988051.973       204387.93
#Sta/Elev= 30
       0  1862.1    22.8  1862.1   38.591860.574    45.6 1858.83    52.2 1858.24
    94.5 1858.98     101 1858.01   107.6 1855.95     113 1855.07   117.4 1854.46
   123.9 1854.12     128 1854.25   136.9 1854.58   140.2 1855.24   143.4 1857.81
   153.2 1867.98     163 1876.53   166.2 1878.54     176  1880.1   185.8  1883.6
   192.3 1886.93   195.6 1889.29   205.4 1898.54   215.2  1906.3   224.9 1911.63
   231.4 1917.31     238 1921.97   254.3 1934.84   257.5 1936.85   260.8    1938
#Mann= 4 ,-1 , 0
       0    .016       0   38.59     .12       0     113    .045       0
     128     .12       0
#XS Ineff= 2 , 0
           89.16 1862.47
Permanent Ineff=
       F       F
Bank Sta=117.4,136.9
XS Rating Curve= 0 ,0
Exp/Cntr=0.3,0.1

Type RM Length L Ch R = 1 ,7616    ,254.2,254.6,254.8
XS GIS Cut Line= 2
      1988281.14      204726.472      1988343.64      204472.999
#Sta/Elev= 30
       0 1858.02     6.5 1854.36     9.8 1853.18   14.041853.155    19.6 1853.85
    26.1 1854.06   50.951853.093    55.5 1852.69    58.7 1851.92    68.5    1847
    72.6 1845.88    81.6 1845.48    87.6 1845.66    91.4 1846.09    94.6 1847.14
   101.2  1850.3   127.3 1853.27   133.8 1854.54   140.3 1857.47   156.6 1866.06
     173 1872.73   195.8 1880.57   208.8 1884.52   215.4 1887.11   228.4 1891.44
   238.2  1895.8   241.5 1896.59     248    1897   251.3 1897.82   261.1 1901.96
#Mann= 5 ,-1 , 0
       0     .12       0   14.04    .016       0   50.95     .12       0
    72.6    .045       0    87.6     .12       0
Bank Sta=72.6,87.6
XS Rating Curve= 0 ,0
Exp/Cntr=0.3,0.1

Type RM Length L Ch R = 1 ,7361.4  ,76.2,76.1,76.1
XS GIS Cut Line= 3
     1988520.723      204811.541     1988569.334      204624.041
     1988496.418       204512.93
#Sta/Elev= 30
       0 1862.67     6.5  1858.2    12.9 1852.22    16.1 1849.98    22.6 1846.69
    25.8 1845.63   28.141845.498    38.7 1846.35   65.261845.716      71 1844.59
    77.5 1841.42    86.4 1839.91    93.6 1838.58    96.8 1838.68   101.4 1839.92
     113 1844.82   116.2 1845.76   125.9 1846.21  167.561849.838   177.6 1850.81
   193.7 1851.32   209.9 1854.48  230.041856.656   242.3 1856.68   268.2 1858.37
     278 1858.34   290.9 1860.14   303.9 1861.36  324.131862.562   326.6 1862.74
#Mann= 8 ,-1 , 0
       0     .12       0   28.14    .016       0   65.26     .12       0
    86.4    .045       0   101.4     .12       0  167.56    .016       0
  230.04     .06       0  324.13     .12       0
Bank Sta=86.4,101.4
XS Rating Curve= 0 ,0
Exp/Cntr=0.3,0.1

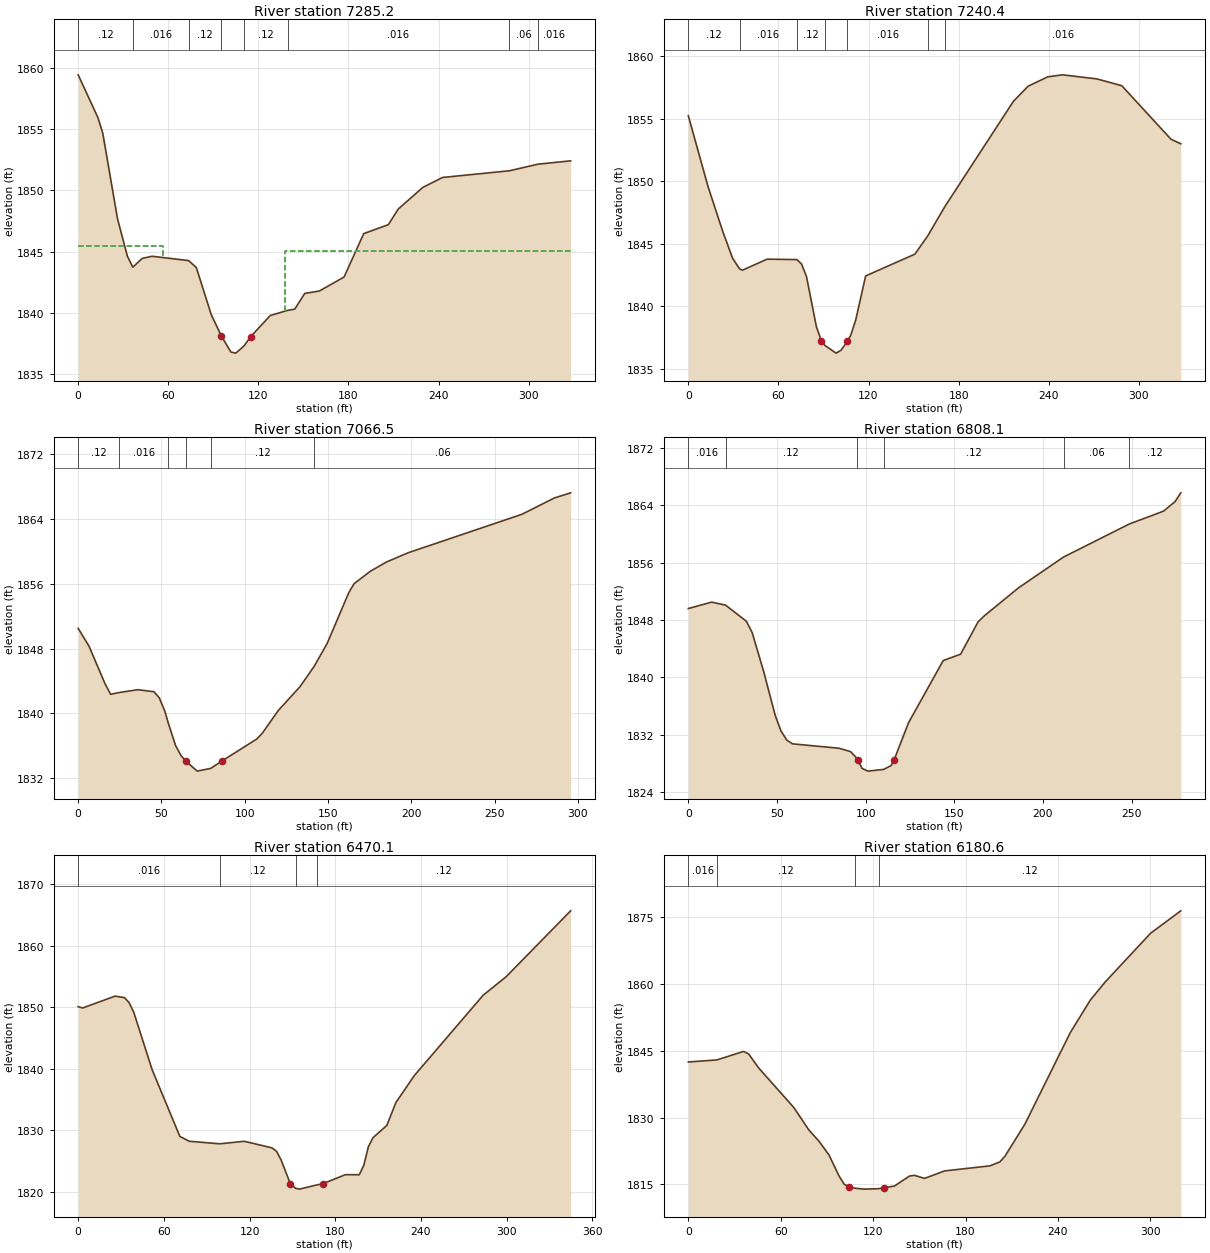
Type RM Length L Ch R = 1 ,7285.2  ,44.8,44.8,44.8
XS GIS Cut Line= 2
     1988591.904      204841.055     1988673.501      204523.347
#Sta/Elev= 30
       0 1859.45    13.1 1855.97    16.4 1854.68    26.2 1847.69    32.8 1844.62
    36.41843.724    42.6 1844.44    49.2 1844.62   73.591844.263    78.7  1843.7
    88.6 1839.86    95.4  1838.1   101.7 1836.79     105  1836.7   110.4 1837.28
   114.8 1838.03   127.9 1839.77  139.451840.194   144.3  1840.3   150.9 1841.58
   160.7 1841.78   177.1 1842.92   190.2 1846.47   206.6  1847.2   213.2 1848.48
   229.6 1850.25   242.7 1851.06  287.211851.605  306.291852.147     328 1852.42
#Mann= 8 ,-1 , 0
       0     .12       0    36.4    .016       0   73.59     .12       0
    95.4    .045       0   110.4     .12       0  139.45    .016       0
  287.21     .06       0  306.29    .016       0
#XS Ineff= 2 , 0
           56.35 1845.47  137.62         1845.01
Permanent Ineff=
       F       F
Bank Sta=95.4,114.8
XS Rating Curve= 0 ,0
Exp/Cntr=0.3,0.1

Type RM Length L Ch R = 1 ,7240.4  ,173.4,174,174.4
XS GIS Cut Line= 2
     1988635.307      204851.472     1988716.904      204533.763
#Sta/Elev= 30
       0 1855.23    13.1 1849.58      23 1845.96    29.5 1843.84   34.16 1842.99
    36.1 1842.89    52.5 1843.77   72.321843.736    75.4 1843.38    78.7 1842.38
    85.3 1838.37    88.6 1837.25    90.9 1836.88    98.4 1836.26   101.7 1836.49
   105.9  1837.2   108.2  1837.7   111.5 1838.91   118.1 1842.43   150.9 1844.17
  159.591845.655  170.791847.958   216.5 1856.38   226.3 1857.59   239.4 1858.34
   249.3  1858.5   272.3 1858.17   288.7 1857.63   321.5 1853.35     328 1852.99
#Mann= 7 ,-1 , 0
       0     .12       0   34.16    .016       0   72.32     .12       0
    90.9    .045       0   105.9    .016       0  159.59     .06       0
  170.79    .016       0
Bank Sta=88.6,105.9
XS Rating Curve= 0 ,0
Exp/Cntr=0.3,0.1

Type RM Length L Ch R = 1 ,7066.5  ,264.5,258.4,251.9
XS GIS Cut Line= 2
     1988803.709      204884.458      1988883.57      204599.736
#Sta/Elev= 30
       0 1850.52     6.5 1848.32    16.2 1843.65    19.5 1842.37   24.451842.584
    35.8 1842.94    45.5 1842.69    48.7 1841.94      52 1840.31   54.081838.835
    58.5 1836.04    61.7 1834.82    64.6 1834.12    71.5 1832.88    79.6 1833.22
   86.071834.096   107.2 1836.84   110.5 1837.54   120.2 1840.38   133.2 1843.31
  141.771845.844   149.5 1848.65   162.5 1854.93   165.7 1856.04   175.5 1857.58
   185.2 1858.72   198.2 1859.86   266.5 1864.61     286 1866.63   295.7 1867.26
#Mann= 6 ,-1 , 0
       0     .12       0   24.45    .016       0   54.08     .12       0
    64.6    .045       0    79.6     .12       0  141.77     .06       0
Bank Sta=64.6,86.07
XS Rating Curve= 0 ,0
Exp/Cntr=0.3,0.1

Type RM Length L Ch R = 1 ,6808.1  ,314.8,338,360.6
XS GIS Cut Line= 2
     1989079.751      204934.805     1989078.015      204657.027
#Sta/Elev= 30
       0  1849.6    13.1 1850.49   20.99 1850.08    32.7 1847.84      36 1846.26
    42.5 1840.83      49 1834.73    52.3 1832.53    55.6 1831.26    58.8 1830.75
      85 1830.14    91.5 1829.67    95.2 1828.72   95.681828.483      98 1827.34
   101.3 1826.95   110.2 1827.19   114.4 1827.72  115.961828.437   124.2 1833.68
   143.8 1842.36   153.6 1843.24   163.4 1847.72   166.7 1848.53   186.3 1852.49
  211.691856.778  248.761861.377     268 1863.16   274.5 1864.48   277.8 1865.72
#Mann= 6 ,-1 , 0
       0    .016       0   20.99     .12       0    95.2    .045       0
   110.2     .12       0  211.69     .06       0  248.76     .12       0
Bank Sta=95.68,115.96
XS Rating Curve= 0 ,0
Exp/Cntr=0.3,0.1

Type RM Length L Ch R = 1 ,6470.1  ,300,289.5,278.7
XS GIS Cut Line= 4
     1989284.612      205049.388     1989336.655        204971.2
     1989453.015      204896.611      1989499.89       204794.18
#Sta/Elev= 30
       0 1850.08     3.2 1849.87    25.9  1851.8    32.4 1851.55    35.6 1850.76
    38.9 1849.19    51.8 1839.82    71.2 1828.98    77.7 1828.19   98.981827.773
   116.4 1828.18   135.7 1827.11   138.9 1826.55   142.1 1825.14   148.6 1821.26
   152.2 1820.54     155  1820.4   167.2 1821.09   171.1 1821.26   187.1 1822.75
   196.8 1822.74     200 1824.28   203.2  1827.3   206.4 1828.76   216.1 1830.76
   222.5  1834.5   235.4 1838.88   283.6 1851.95   299.7 1854.96   344.8 1865.67
#Mann= 4 ,-1 , 0
       0    .016       0   98.98     .12       0   152.2    .045       0
   167.2     .12       0
Bank Sta=148.6,171.1
XS Rating Curve= 0 ,0
Exp/Cntr=0.3,0.1

Type RM Length L Ch R = 1 ,6180.6  ,298.1,299.6,300.8
XS GIS Cut Line= 2
     1989551.973      205219.527     1989713.432      204943.486
#Sta/Elev= 30
       0 1842.48   18.561842.942    35.9 1844.85    39.2 1844.27    45.7 1841.13
    68.5 1832.26    78.3  1827.2    84.8 1824.72    91.4 1821.57    97.9 1816.86
   101.2 1815.05   104.4 1814.38   108.5 1814.13   114.2 1813.93   123.5 1814.02
   127.3 1814.26   133.8 1814.61   143.6 1816.86   146.8 1817.03   153.4 1816.34
   166.4 1818.02   195.8 1819.15   202.3 1820.04   205.6 1821.31   218.6 1828.54
     248 1849.05   261.1  1856.4   270.8 1860.48   300.2 1871.39   319.8 1876.42
#Mann= 4 ,-1 , 0
       0    .016       0   18.56     .12       0   108.5    .045       0
   123.5     .12       0
Bank Sta=104.4,127.3
XS Rating Curve= 0 ,0
Exp/Cntr=0.3,0.1

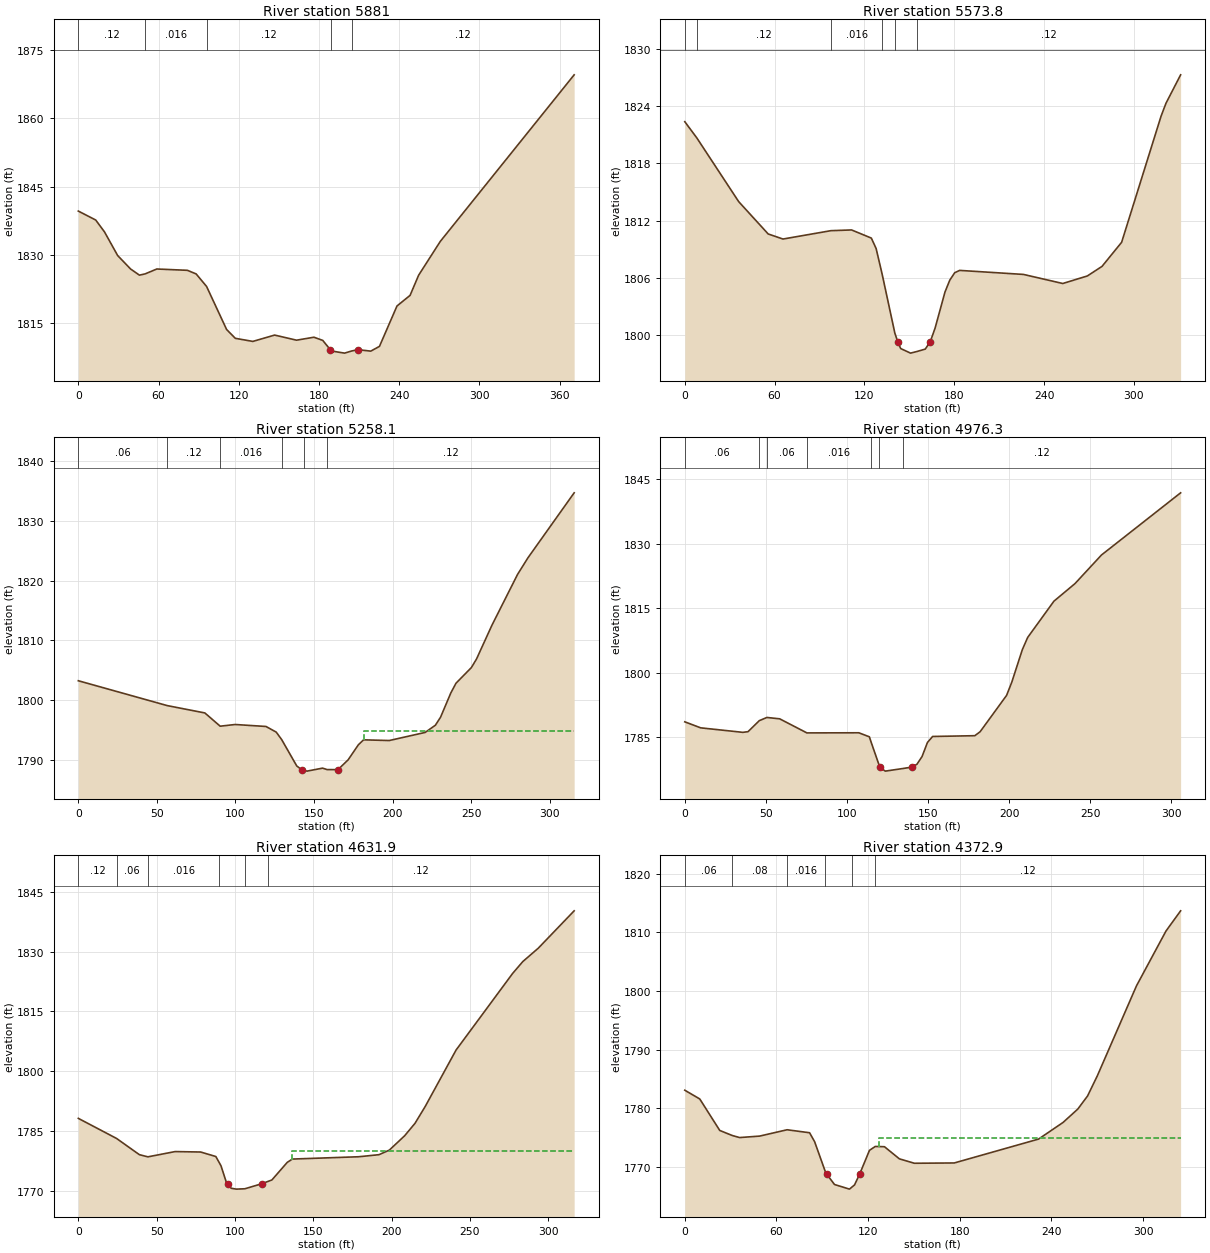
Type RM Length L Ch R = 1 ,5881    ,302.2,307.2,310.5
XS GIS Cut Line= 4
     1989694.334      205436.541     1989782.876      205394.874
     1989866.209      205269.874     1989975.584      205214.319
#Sta/Elev= 30
       0 1839.62      13 1837.66    19.6 1835.04    29.4 1829.87    39.1 1826.91
    45.7 1825.56   49.981825.841    58.7 1826.91    81.6 1826.62    88.1 1825.83
   95.921823.078   110.9 1813.63   117.4  1811.7   130.5 1811.02   146.8 1812.41
   163.2 1811.29   176.2 1811.94   182.8 1811.24  188.391809.221   189.3 1808.92
   199.1 1808.45   204.3 1808.91   208.9 1809.21   218.7 1808.89   225.2 1809.93
   238.3 1818.79   248.1 1821.13   254.5 1825.55   270.7 1832.97   370.8 1869.52
#Mann= 5 ,-1 , 0
       0     .12       0   49.98    .016       0   95.92     .12       0
   189.3    .045       0   204.3     .12       0
Bank Sta=188.39,208.9
XS Rating Curve= 0 ,0
Exp/Cntr=0.3,0.1

Type RM Length L Ch R = 1 ,5573.8  ,315.3,315.7,315.4
XS GIS Cut Line= 3
     1989873.154      205634.458      1989968.64      205599.736
     1990128.362      205434.805
#Sta/Elev= 30
       0 1822.35    8.041820.652      36 1813.99    55.7 1810.61    65.6 1810.08
    97.61810.954   111.4 1811.03   124.6 1810.18   127.8 1809.09  131.791806.431
   140.3 1800.25   142.21799.361   144.2 1798.63   150.8 1798.15   155.3 1798.33
   160.6 1798.57   163.9 1799.32   167.2 1800.77   173.8 1804.54     177 1805.78
   180.3 1806.56   183.6  1806.8   226.2 1806.38   252.5 1805.43   268.9 1806.22
   278.7 1807.22   291.8 1809.74   318.1 1822.91   321.4 1824.27   331.2 1827.25
#Mann= 6 ,-1 , 0
       0     .06       0    8.04     .12       0    97.6    .016       0
  131.79     .12       0   140.3    .045       0   155.3     .12       0
Bank Sta=142.2,163.9
XS Rating Curve= 0 ,0
Exp/Cntr=0.3,0.1

Type RM Length L Ch R = 1 ,5258.1  ,281.2,281.8,282.2
XS GIS Cut Line= 3
     1990117.945       205856.68     1990204.751      205801.124
      1990352.32      205648.347
#Sta/Elev= 30
       0 1803.22   56.521799.054    80.5 1797.82   90.261795.598    99.8 1795.88
   119.4 1795.55   125.9 1794.61   129.41793.347     139 1788.92   142.3 1788.27
   143.3  1788.2   145.5 1788.06   155.4 1788.56   158.3 1788.32   165.2 1788.31
   171.7 1789.96   178.2 1792.48   181.5 1793.31   197.8 1793.19   220.7 1794.55
   227.2 1795.76   230.5 1797.11     237 1801.16   240.3  1802.8   250.1 1805.43
   253.4 1806.88   263.2 1812.54   279.5 1821.06   286.1 1823.84   315.5 1834.74
#Mann= 6 ,-1 , 0
       0     .06       0   56.52     .12       0   90.26    .016       0
   129.4     .12       0   143.3    .045       0   158.3     .12       0
#XS Ineff= 2 , 0
                          182.04          1794.8
Permanent Ineff=
       F       F
Bank Sta=142.3,165.2
XS Rating Curve= 0 ,0
Exp/Cntr=0.3,0.1

Type RM Length L Ch R = 1 ,4976.3  ,345,344.4,343.4
XS GIS Cut Line= 2
      1990352.32      206047.652     1990569.334      205832.374
#Sta/Elev= 30
       0 1788.53     9.8 1787.13    35.8 1786.08      39 1786.24   45.921788.799
    50.61789.547    58.5 1789.23   75.281785.951   107.3 1785.98   113.8 1785.04
  115.031783.639   119.5 1778.78   120.3 1777.94   123.6 1777.05   134.5 1777.66
   139.8 1777.97   143.1 1778.64   146.3 1780.46   149.6 1783.72   152.8 1785.12
   178.8  1785.3   182.1 1786.23   198.4 1794.69   201.6 1797.76   208.1 1805.33
   211.4 1808.18   227.6 1816.63   240.6 1820.73   256.9 1827.38   305.7 1841.86
#Mann= 7 ,-1 , 0
       0     .06       0   45.92     .12       0    50.6     .06       0
   75.28    .016       0  115.03     .12       0   119.5    .045       0
   134.5     .12       0
Bank Sta=120.3,139.8
XS Rating Curve= 0 ,0
Exp/Cntr=0.3,0.1

Type RM Length L Ch R = 1 ,4631.9  ,253.4,259,263.4
XS GIS Cut Line= 3
     1990630.098      206257.722     1990756.834      206122.305
     1990772.459      205992.097
#Sta/Elev= 30
       0 1788.14   24.391783.102      39 1779.02   44.411778.476    61.8  1779.8
    78.1 1779.69    87.8 1778.56   90.061776.964    91.1 1776.23    94.4 1772.21
    95.51771.653    97.6 1770.59   100.9 1770.37   106.41770.463   117.1 1771.72
   121.41772.347   123.6 1772.67   133.4 1777.09   136.7 1777.92     179  1778.5
     192 1779.02   198.6 1780.17   208.4 1783.79     215 1786.91   221.5 1791.13
   241.2  1805.3   277.3 1824.53   283.8 1827.51   293.7 1830.88   316.6 1840.26
#Mann= 6 ,-1 , 0
       0     .12       0   24.39     .06       0   44.41    .016       0
   90.06     .12       0   106.4    .045       0   121.4     .12       0
#XS Ineff= 2 , 0
                          136.17            1780
Permanent Ineff=
       F       F
Bank Sta=95.5,117.1
XS Rating Curve= 0 ,0
Exp/Cntr=0.3,0.1

Type RM Length L Ch R = 1 ,4372.9  ,243.5,239.3,234.2
XS GIS Cut Line= 3
     1990805.651      206410.154     1990980.776         206290.
     1991041.351      206195.567
#Sta/Elev= 30
       0 1783.09     9.8  1781.6    22.9 1776.23   31.131775.365    35.9 1775.02
      49 1775.27   66.961776.349    81.7 1775.84      85 1774.31   92.071769.158
   93.051768.724      98 1767.02   107.8 1766.23   109.71766.639   111.1 1766.94
   114.4 1768.75   120.9 1772.84   124.71773.504   130.7 1773.46   140.5 1771.39
   150.3 1770.64   176.4 1770.69   231.6 1774.76   247.6 1777.59   257.3 1779.88
   263.7 1782.12   270.1 1785.56   295.7 1800.88     315 1810.22   324.6 1813.67
#Mann= 6 ,-1 , 0
       0     .06       0   31.13     .08       0   66.96    .016       0
   92.07     .12       0   109.7    .045       0   124.7     .12       0
#XS Ineff= 2 , 0
                          127.14            1775
Permanent Ineff=
       F       F
Bank Sta=93.05,114.4
XS Rating Curve= 0 ,0
Exp/Cntr=0.3,0.1

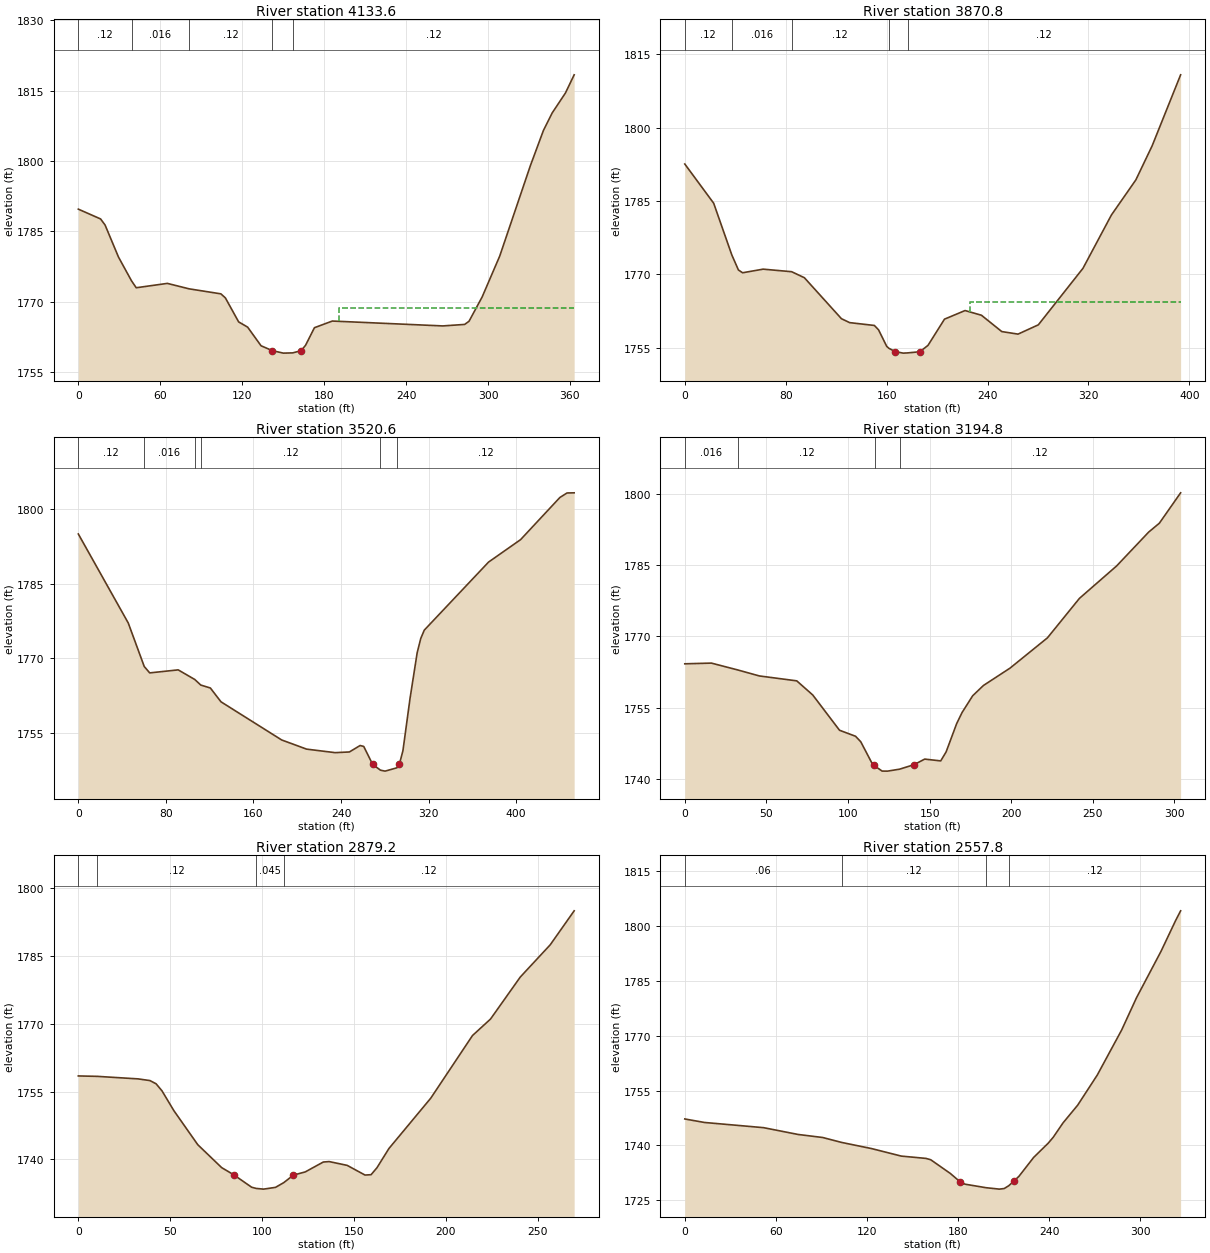
Type RM Length L Ch R = 1 ,4133.6  ,269.1,262.9,256.8
XS GIS Cut Line= 3
      1990998.87      206568.833     1991157.724       206404.77
     1991211.109      206281.072
#Sta/Elev= 30
       0 1789.74    16.3 1787.65    19.6 1786.35    29.4 1779.53   38.961774.452
    42.4 1772.98    65.2 1773.91   81.161772.745   104.4 1771.68   107.7 1770.81
   117.4  1765.7     124 1764.58   133.8 1760.61     142 1759.58   150.1 1759.04
     157 1759.09   163.1 1759.56   166.4 1760.71   172.9 1764.46     186 1765.88
   266.9 1764.84   282.9 1765.16   286.1 1765.83   295.7    1771   308.6 1779.74
     331 1798.98   340.6 1806.52     347 1810.25   356.7  1814.5   363.1 1818.38
#Mann= 5 ,-1 , 0
       0     .12       0   38.96    .016       0   81.16     .12       0
     142    .045       0     157     .12       0
#XS Ineff= 2 , 0
                          191.12         1768.68
Permanent Ineff=
       F       F
Bank Sta=142,163.1
XS Rating Curve= 0 ,0
Exp/Cntr=0.3,0.1

Type RM Length L Ch R = 1 ,3870.8  ,345.1,350.1,355
XS GIS Cut Line= 3
     1991229.339      206769.354     1991337.412      206571.437
     1991457.203      206454.249
#Sta/Elev= 30
       0 1792.54    22.9 1784.52   37.271773.945    42.5 1770.87    45.8 1770.29
    62.1 1771.03    84.71770.508    94.8 1769.28   124.2 1760.89   130.7 1760.09
   150.3 1759.51   153.6 1758.62   160.1 1755.23   161.8 1754.84   166.7 1754.17
   173.2 1753.85   176.8  1753.9   186.3 1754.13   192.8 1755.43   205.9  1760.8
   222.2 1762.56   235.2  1761.6   251.3 1758.26   264.2 1757.74   280.3 1759.64
   315.7 1771.21   338.3 1782.14   357.6 1789.29   370.5 1796.25   393.1 1810.79
#Mann= 5 ,-1 , 0
       0     .12       0   37.27    .016       0    84.7     .12       0
   161.8    .045       0   176.8     .12       0
#XS Ineff= 2 , 0
                          226.21         1764.31
Permanent Ineff=
       F       F
Bank Sta=166.7,186.3
XS Rating Curve= 0 ,0
Exp/Cntr=0.3,0.1

Type RM Length L Ch R = 1 ,3520.6  ,328.1,325.9,322.5
XS GIS Cut Line= 2
      1991437.39      206979.944     1991734.265       206637.93
#Sta/Elev= 30
       0    1795    45.6 1777.08    60.21768.322    65.2 1767.03    91.2 1767.64
  106.32 1765.71  111.851764.581   120.6 1763.99   130.3 1761.21   185.7 1753.53
   208.5 1751.68   234.6 1750.97   247.6 1751.11   257.4 1752.41   260.7 1752.22
  268.861748.596     276 1747.44   280.2 1747.25     291 1747.92   293.2 1748.59
   296.5 1751.36     303 1761.91   309.5 1771.08   312.8 1773.97     316 1775.64
   374.7 1789.34     404 1793.87   439.9 1802.36   446.4 1803.26   452.9 1803.29
#Mann= 6 ,-1 , 0
       0     .12       0    60.2    .016       0  106.32     .06       0
  111.85     .12       0     276    .045       0     291     .12       0
Bank Sta=268.86,293.2
XS Rating Curve= 0 ,0
Exp/Cntr=0.3,0.1

Type RM Length L Ch R = 1 ,3194.8  ,316.4,315.6,314.7
XS GIS Cut Line= 2
      1991727.32       207137.93     1991897.459      206886.194
#Sta/Elev= 30
       0 1764.26    16.3 1764.41   32.391762.975    45.7 1761.71    68.6 1760.68
    78.4 1757.71    94.8  1750.3   104.6 1749.04   107.8 1747.89   114.4 1743.57
  115.681743.087   116.6 1742.74   120.9 1741.72   124.2 1741.71   131.6 1742.12
   140.5 1743.07     147 1744.24   156.8 1743.86   160.1 1745.74   166.6 1751.71
   169.9 1754.03   176.4 1757.55     183 1759.71   199.3 1763.36   222.2 1769.72
   241.8 1778.01   264.6 1784.83   284.2 1791.93   290.8 1793.82   303.8 1800.19
#Mann= 4 ,-1 , 0
       0    .016       0   32.39     .12       0   116.6    .045       0
   131.6     .12       0
Bank Sta=115.68,140.5
XS Rating Curve= 0 ,0
Exp/Cntr=0.3,0.1

Type RM Length L Ch R = 1 ,2879.2  ,320.2,321.4,321.9
XS GIS Cut Line= 2
     1992006.834       207294.18     1992149.195      207065.013
#Sta/Elev= 30
       0 1758.47   10.22 1758.38    32.5 1757.82      39 1757.44    42.3 1756.74
    45.5 1755.19      52 1750.79      65 1743.27      78  1738.2    84.5 1736.64
    94.3 1733.87    96.8  1733.6   100.8 1733.45   107.3 1733.84   111.8 1734.89
     117 1736.54   123.5 1737.26   133.3 1739.44   136.5 1739.54   146.3  1738.7
     156 1736.56   159.3 1736.64   162.5 1738.18     169 1742.42   191.8 1753.57
   214.5 1767.41   224.3 1771.05   240.5 1780.34   256.8 1787.47   269.8 1794.97
#Mann= 4 ,-1 , 0
       0     .06       0   10.22     .12       0    96.8    .045       0
   111.8     .12       0
Bank Sta=84.5,117
XS Rating Curve= 0 ,0
Exp/Cntr=0.3,0.1

Type RM Length L Ch R = 1 ,2557.8  ,328.7,343.1,357.1
XS GIS Cut Line= 3
     1992178.709      207389.666      1992321.07      207380.986
     1992423.501      207228.208
#Sta/Elev= 30
       0 1747.24      13 1746.28    51.9 1744.86    74.6    1743    90.8 1742.17
   103.3 1740.82   123.2 1739.12   142.6 1737.08   158.8 1736.45     162 1736.08
   174.9 1732.33   181.4 1730.03   184.6 1729.39   198.4 1728.43   207.2 1728.04
   210.4  1728.2   213.4 1728.97   216.8 1730.25   220.1 1731.54   229.8 1736.72
   239.4 1740.62   242.7 1742.24   249.1 1746.14   258.8 1751.02   271.7 1759.26
   287.8 1771.62   297.5 1780.38   313.7 1793.13   323.3 1801.54   326.6  1804.2
#Mann= 4 ,-1 , 0
       0     .06       0   103.3     .12       0   198.4    .045       0
   213.4     .12       0
Bank Sta=181.4,216.8
XS Rating Curve= 0 ,0
Exp/Cntr=0.3,0.1

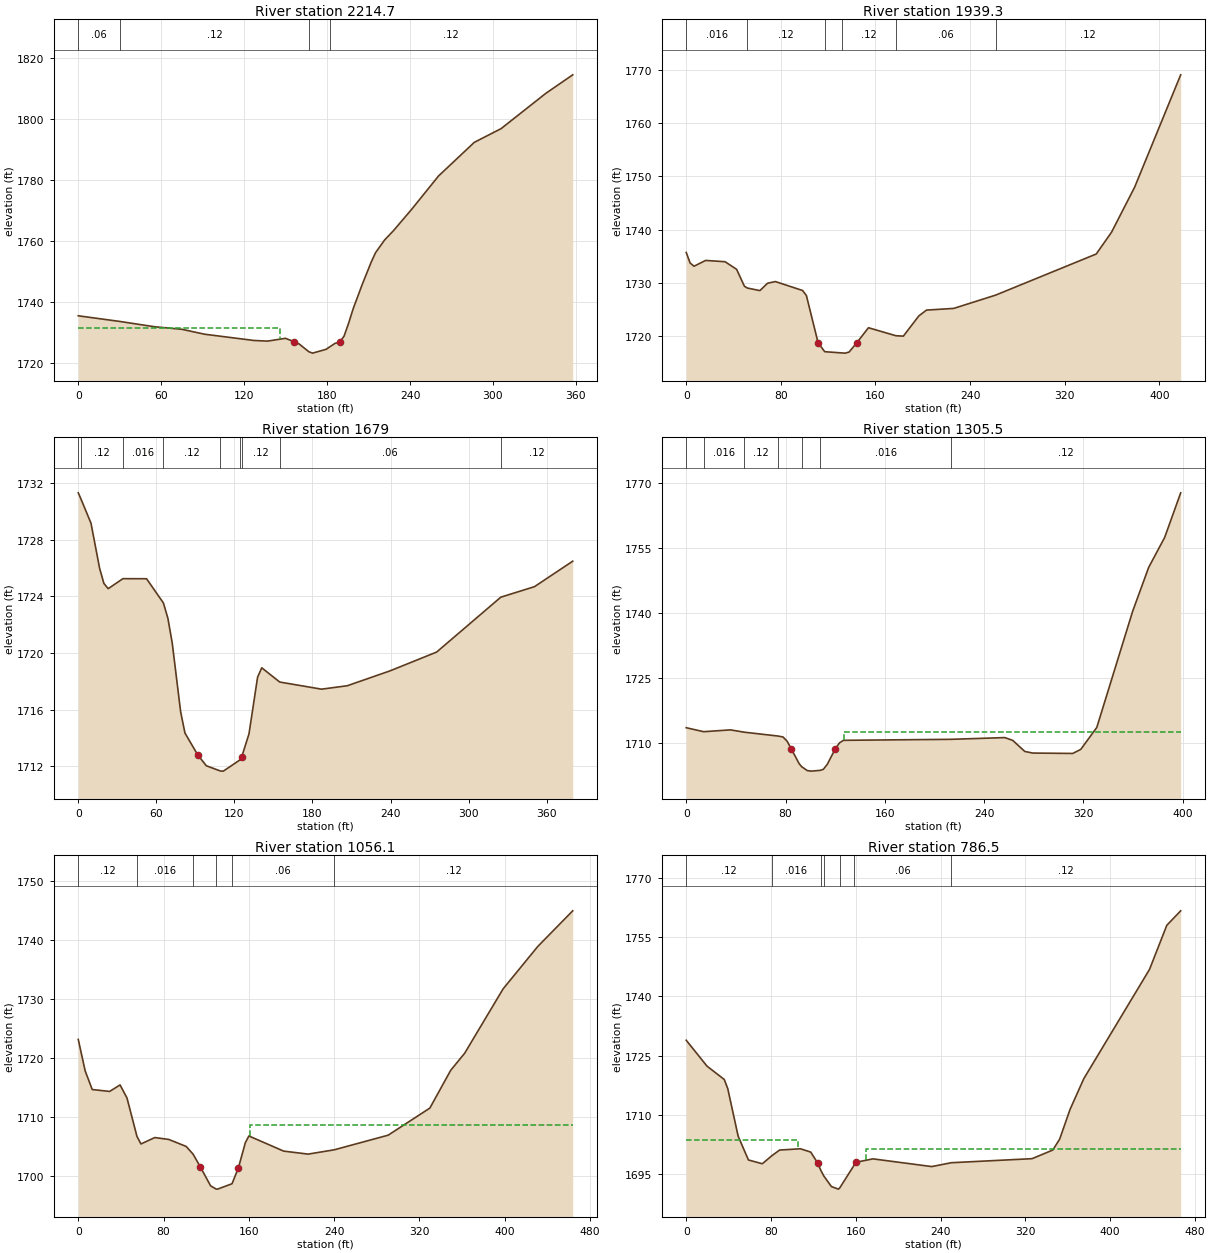
Type RM Length L Ch R = 1 ,2214.7  ,280.6,275.3,269.8
XS GIS Cut Line= 3
     1992428.709      207615.361     1992654.404      207530.291
     1992706.487      207426.124
#Sta/Elev= 30
       0 1735.38   30.29 1733.51    55.4 1731.77      75 1730.95    91.3 1729.34
   127.1 1727.28   136.9 1727.07   149.9 1727.99   156.4 1726.83   159.7 1726.17
   166.8 1723.59   169.5 1723.13   179.3 1724.38   181.8 1725.15   185.8 1726.35
     189 1726.68   192.3 1728.72   195.6 1732.98   198.8 1737.61   205.3 1745.52
   211.9 1752.98   215.1 1756.11   221.6 1760.25   228.2  1763.4   241.2 1770.32
   260.6 1781.24   286.5 1792.29   305.9 1796.79   338.2 1808.35   357.7 1814.44
#Mann= 4 ,-1 , 0
       0     .06       0   30.29     .12       0   166.8    .045       0
   181.8     .12       0
#XS Ineff= 2 , 0
          145.72 1731.32
Permanent Ineff=
       F       F
Bank Sta=156.4,189
XS Rating Curve= 0 ,0
Exp/Cntr=0.3,0.1

Type RM Length L Ch R = 1 ,1939.3  ,263.1,260.4,256.2
XS GIS Cut Line= 3
     1992560.654      207882.722     1992784.612      207728.208
     1992854.057      207599.736
#Sta/Elev= 30
       0 1735.69     3.3  1733.7     6.6  1733.1    16.4 1734.19    32.8 1733.95
    42.6 1732.52    49.2 1729.33   51.73 1728.99    62.3 1728.51    68.8  1729.9
    75.4 1730.21    98.4 1728.53   101.6 1727.59   111.5  1718.7   117.1 1717.01
   132.1 1716.77   134.4 1716.74   137.7 1716.94   144.2 1718.69   154.1 1721.52
  177.271720.016   183.6 1719.94   196.7 1723.75   203.2 1724.84   226.2 1725.16
  261.661727.663   346.7  1735.4   359.7 1739.53   379.2    1748   418.1 1769.13
#Mann= 6 ,-1 , 0
       0    .016       0   51.73     .12       0   117.1    .045       0
   132.1     .12       0  177.27     .06       0  261.66     .12       0
Bank Sta=111.5,144.2
XS Rating Curve= 0 ,0
Exp/Cntr=0.3,0.1

Type RM Length L Ch R = 1 ,1679    ,379.7,373.5,366.7
XS GIS Cut Line= 3
      1992749.89      208077.166     1992923.501      207912.236
     1992966.904      207778.555
#Sta/Elev= 30
       0 1731.31    1.981730.896     9.8 1729.16    16.4 1725.98    19.7 1724.91
      23 1724.54   34.341725.246    52.5 1725.24   65.441723.529    68.9 1722.44
    72.2 1720.71    78.7 1715.83      82 1714.34    91.8  1712.8    98.4 1712.03
   109.31711.657   111.5 1711.65   124.31712.445   125.7 1712.68   131.2 1714.28
   137.8 1718.28     141 1718.95  154.841717.943     187 1717.44   206.7 1717.68
   239.5 1718.73   275.4 1720.06  324.76 1723.94   350.6 1724.68     380 1726.48
#Mann= 9 ,-1 , 0
       0     .06       0    1.98     .12       0   34.34    .016       0
   65.44     .12       0   109.3    .045       0   124.3     .06       0
   125.7     .12       0  154.84     .06       0  324.76     .12       0
Bank Sta=91.8,125.7
XS Rating Curve= 0 ,0
Exp/Cntr=0.3,0.1

Type RM Length L Ch R = 1 ,1305.5  ,244.2,249.5,254.7
XS GIS Cut Line= 3
      1993058.05      208331.506     1993186.522      208109.284
     1993301.105      208025.951
#Sta/Elev= 30
       0 1713.52   14.021712.602    35.7 1713.02   46.841712.485   73.981711.597
      78 1711.38    81.2 1710.44    84.5 1708.72      91 1705.21      93 1704.53
    97.5 1703.63   100.7  1703.5     108 1703.68   110.5 1703.92   113.7  1705.1
   120.2  1708.7   123.5 1710.02   126.7 1710.61  213.42 1710.84   256.7 1711.24
   263.1 1710.59   272.8 1708.04   279.2 1707.67   311.4 1707.58   317.9 1708.52
   330.8 1713.58   359.7 1740.39   372.6 1750.52   385.5 1757.44   398.4 1767.73
#Mann= 7 ,-1 , 0
       0     .12       0   14.02    .016       0   46.84     .12       0
   73.98    .016       0      93    .045       0     108    .016       0
  213.42     .12       0
#XS Ineff= 2 , 0
                          127.14         1712.42
Permanent Ineff=
       F       F
Bank Sta=84.5,120.2
XS Rating Curve= 0 ,0
Exp/Cntr=0.3,0.1

Type RM Length L Ch R = 1 ,1056.1  ,271.6,269.5,267.5
XS GIS Cut Line= 3
     1993198.342      208509.815     1993417.933      208277.133
     1993539.285      208200.073
#Sta/Elev= 30
       0 1723.17     6.5 1717.84    13.1  1714.7    29.4 1714.38    39.2 1715.48
    45.7 1713.27   55.061706.771    58.8  1705.5    71.8 1706.58    84.9 1706.26
   101.2 1705.08  107.681703.775   114.3 1701.68   124.1 1698.42   129.2 1697.88
   130.6 1697.86   144.2 1698.77   150.2 1701.47   156.7 1705.72     160 1706.85
   192.6 1704.29   215.5 1703.78  240.071704.509   290.6 1706.98   329.7 1711.56
   349.3 1717.96   362.4 1720.85   398.4 1731.72     431 1738.91   463.7 1744.92
#Mann= 6 ,-1 , 0
       0     .12       0   55.06    .016       0  107.68     .12       0
   129.2    .045       0   144.2     .06       0  240.07     .12       0
#XS Ineff= 2 , 0
                          160.99         1708.75
Permanent Ineff=
       F       F
Bank Sta=114.3,150.2
XS Rating Curve= 0 ,0
Exp/Cntr=0.3,0.1

Type RM Length L Ch R = 1 ,786.5   ,334.4,336,337.6
XS GIS Cut Line= 3
     1993392.099      208714.666     1993609.547      208437.322
     1993705.901      208376.124
#Sta/Elev= 30
       0 1728.91    19.6 1722.36    35.9 1718.98    39.2 1716.66      49 1704.63
    58.7  1698.6    71.8 1697.65    80.81699.677    88.1 1701.11   107.7 1701.44
   117.5  1700.6     124 1697.85  126.951696.026   129.8 1694.56     137 1691.87
   143.6 1691.22   144.8  1691.5  158.331697.229   159.9    1698   176.2 1698.88
   231.7 1696.93  250.191697.906   326.3 1698.93   345.9 1701.11   352.4 1703.88
   362.2  1711.4   375.2  1719.2   437.2 1746.86   453.5 1758.02   466.6 1761.68
#Mann= 7 ,-1 , 0
       0     .12       0    80.8    .016       0  126.95     .12       0
   129.8    .045       0   144.8     .12       0  158.33     .06       0
  250.19     .12       0
#XS Ineff= 2 , 0
          105.26 1703.65  169.76         1701.49
Permanent Ineff=
       F       F
Bank Sta=124,159.9
XS Rating Curve= 0 ,0
Exp/Cntr=0.3,0.1