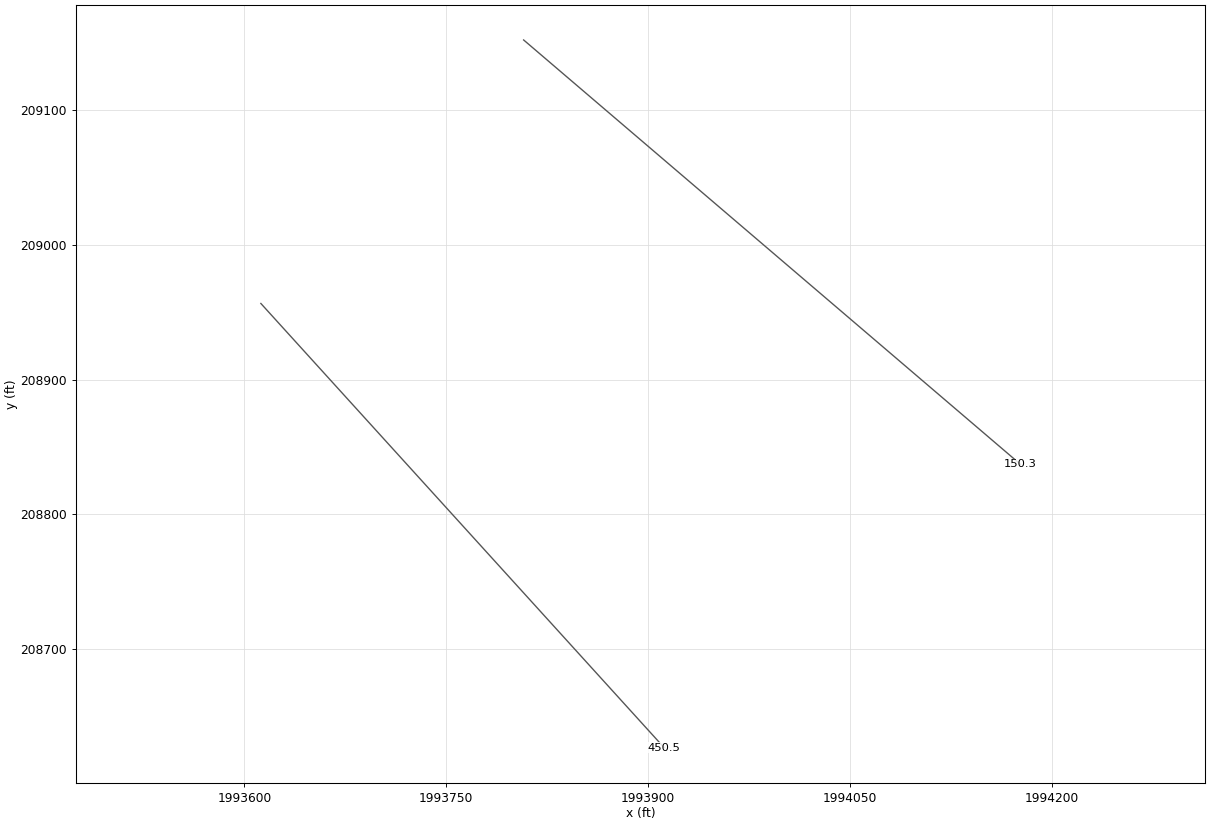
HEC-RAS study PIPESTCK.prj: PIPESTCK

--- PIPESTCK.g01 (geometry) --- (continued)

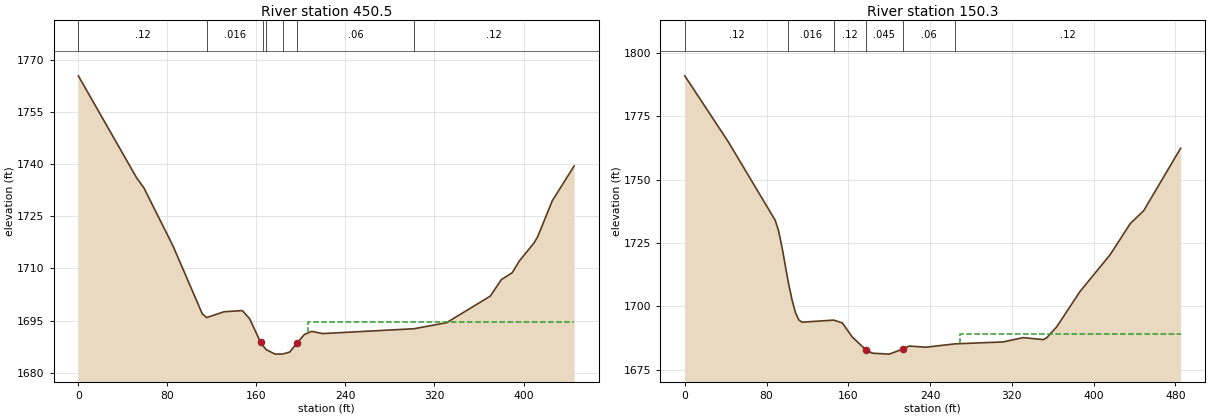
Type RM Length L Ch R = 1 ,450.5   ,297.4,300.3,303.1
XS GIS Cut Line= 2
     1993612.289      208956.665     1993911.768      208626.804
#Sta/Elev= 30
       0 1765.45    52.4 1736.09      59 1733.15    85.2 1716.39   111.4 1696.93
  115.35 1695.87     131 1697.54   147.4 1697.88     154 1695.49   163.8  1688.7
  165.951687.736   168.9  1686.6   176.9 1685.34   183.9 1685.38     190 1685.96
   196.6 1688.56  196.671688.591   203.1 1690.99   209.7 1691.89   219.5 1691.26
  301.641692.652   330.9 1694.39   370.2 1702.05     380 1706.77   389.8 1708.76
   396.4 1712.22   409.5 1717.38   412.8  1719.2   425.9 1729.52   445.5 1739.49
#Mann= 7 ,-1 , 0
       0     .12       0  115.35    .016       0  165.95     .12       0
   168.9    .045       0   183.9     .12       0  196.67     .06       0
  301.64     .12       0
#XS Ineff= 2 , 0
                           206.4          1694.7
Permanent Ineff=
       F       F
Bank Sta=163.8,196.6
XS Rating Curve= 0 ,0
Exp/Cntr=0.3,0.1

Type RM Length L Ch R = 1 ,150.3   ,162.9,150.3,137
XS GIS Cut Line= 2
     1993807.464      209152.383     1994176.387      208837.279
#Sta/Elev= 30
       0 1790.96    42.6 1764.93    88.5 1733.97    91.8  1729.8    95.1 1723.42
  101.251709.658   104.9 1702.65   108.2 1697.72   111.5 1694.73   114.7 1693.81
  145.671694.621   154.1 1693.55   163.9 1687.96     177 1682.99   183.6 1681.58
     200 1681.21   213.1 1683.15   219.6  1684.4     236 1683.94  264.311685.256
   311.4 1686.02   331.1 1687.72   350.8 1686.93     354 1687.59   363.9 1691.95
   386.8 1705.95   416.3 1720.45     436 1732.74   449.1  1737.8   485.2  1762.4
#Mann= 6 ,-1 , 0
       0     .12       0  101.25    .016       0  145.67     .12       0
     177    .045       0   213.1     .06       0  264.31     .12       0
#XS Ineff= 2 , 0
                          269.35         1689.12
Permanent Ineff=
       F       F
Bank Sta=177,213.1
XS Rating Curve= 0 ,0
Exp/Cntr=0.3,0.1

Chan Stop Cuts=-1
Use User Specified Reach Order=0
Composite Channel Slope=5